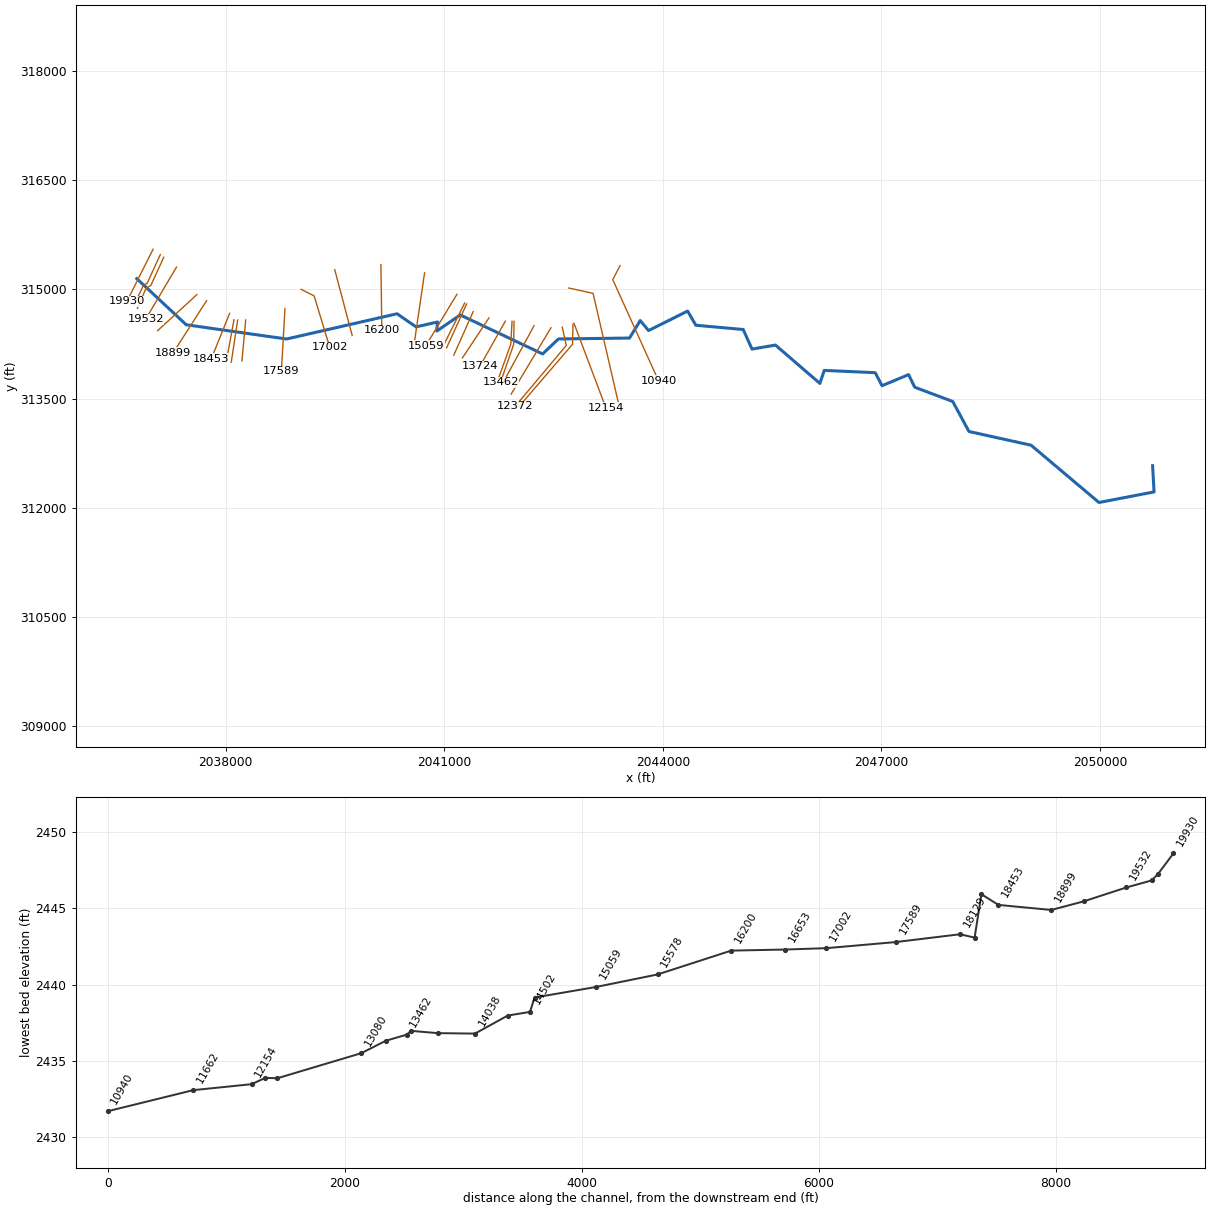
--- BUFFALOCK.prj (project) ---

Proj Title=BUFFALOCK
Current Plan=p01
Default Exp/Contr=0.3,0.1
English Units
Geom File=g01
Flow File=f01
Plan File=p01
Y Axis Title=Elevation
X Axis Title(PF)=Main Channel Distance
X Axis Title(XS)=Station
BEGIN DESCRIPTION:
Stream Name- Buffalo Creek
Flood Zone: Zone A
Greenbrier County, WV
County-Wide Study
WVDHSEM-2018-3, Flood Risk Project
HEC-RAS Version: 5.0.7
General Notes:
For the Hydrology regression was used.
END DESCRIPTION:
DSS File=dss
DSS Export Rating Curves= 0
DSS Export Rating Curve Sorted= 0
DSS Export Volume Flow Curves= 0
DXF Filename=..\H2c.
DXF OffsetX= 0
DXF OffsetY= 0
DXF ScaleX= 1
DXF ScaleY= 10

--- BUFFALOCK.p01 (plan) ---

Plan Title=Floodplain
Program Version=5.07
Short Identifier=Floodplain
Geom File=g01
Flow File=f01
Subcritical Flow
K Sum by GR= 0
Std Step Tol= 0.01
Critical Tol= 0.01
Num of Std Step Trials= 20
Max Error Tol= 0.3
Flow Tol Ratio= 0.001
Split Flow NTrial= 30
Split Flow Tol= 0.02
Split Flow Ratio= 0.02
Log Output Level= 0
Friction Slope Method= 1
Unsteady Friction Slope Method= 2
Unsteady Bridges Friction Slope Method= 1
Parabolic Critical Depth
Global Vel Dist= 0 , 0 , 0
Global Log Level= 0
CheckData=True
Encroach Param=-1 ,0,0, 0
Computation Interval=1MIN
Output Interval=1HOUR
Instantaneous Interval=1HOUR
Mapping Interval=1HOUR
Computation Time Step Use Courant=        0
Computation Time Step Use Time Series=    0
Computation Time Step Count To Double=0
Computation Time Step Max Doubling=0
Computation Time Step Max Halving=0
Computation Time Step Residence Courant=0
Run HTab= 0
Run UNet= 0
Run Sediment= 0
Run PostProcess= 0
Run WQNet= 0
Run RASMapper=-1
UNET Theta= 1
UNET Theta Warmup= 1
UNET ZTol= 0.02
UNET ZSATol= 0.02
UNET MxIter= 20
UNET Max Iter WO Improvement= 0
UNET MaxInSteps= 0
UNET DtIC= 0
UNET DtMin= 0
UNET MaxCRTS= 20
UNET WFStab= 2
UNET SFStab= 1
UNET WFX= 1
UNET SFX= 1
UNET 1D Methodology=Finite Difference
UNET DSS MLevel= 4
UNET Pardiso=0
UNET DZMax Abort= 100
UNET Use Existing IB Tables=-1
UNET Froude Reduction=False
UNET Froude Limit= 0.8
UNET Froude Power= 4
UNET D1 Cores= 0
UNET D2 Coriolis=0
UNET D2 Cores= 0
UNET D2 Theta= 1
UNET D2 Theta Warmup= 1
UNET D2 Z Tol= 0.01
UNET D2 Volume Tol= 0.01
UNET D2 Max Iterations= 20
UNET D2 Equation= 0
UNET D2 RampUpFraction=0.1
UNET D2 TimeSlices= 1
UNET D2 BCVolumeCheck=0
UNET D1D2 MaxIter= 0
UNET D1D2 ZTol=0.01
UNET D1D2 QTol=0.1
UNET D1D2 MinQTol=1
DSS File=dss
Write IC File= 0
Write IC File at Fixed DateTime=0
Write IC File at Sim End=0
Echo Input=False
Echo Parameters=False
Echo Output=False
Write Detailed= 0
HDF Write Warmup=0
HDF Write Time Slices=0
HDF Flush=0
HDF Face Node Velocities=0
HDF Compression= 1
HDF Chunk Size= 1
HDF Spatial Parts= 1
HDF Use Max Rows=0
HDF Fixed Rows= 1
Calibration Method= 0
Calibration Iterations= 20
Calibration Max Change=0.05
Calibration Tolerance=0.2
Calibration Maximum=1.5
Calibration Minimum=0.5
Calibration Optimization Method= 1
WQ AD Non Conservative
WQ ULTIMATE=-1
WQ Max Comp Step=1HOUR
WQ Output Interval=15MIN
WQ Output Selected Increments= 0
WQ Output face flow=0
WQ Output face velocity=0
WQ Output face area=0
WQ Output face dispersion=0
WQ Output cell volume=0
WQ Output cell surface area=0
WQ Output cell continuity=0
WQ Output cumulative cell continuity=0
WQ Output face conc=0
WQ Output face dconc_dx=0
WQ Output face courant=0
WQ Output face peclet=0
WQ Output face adv mass=0
WQ Output face disp mass=0
WQ Output cell mass=0
WQ Output cell source sink temp=0
WQ Output nsm pathways=0
WQ Output nsm derived pathways=0
WQ Output MaxMinRange=-1
WQ Daily Max Min Mean=-1
WQ Daily Range=0
WQ Daily Time=0
WQ Create Restart=0
WQ Fixed Restart=0
WQ System Summary=0
WQ Write To DSS=0
WQ Use Fixed Temperature=0
Sorting and Armoring Iterations= 10
XS Update Threshold= 0.02
Bed Roughness Predictor= 0
Hydraulics Update Threshold= 0.02
Energy Slope Method= 1
Volume Change Method= 1
Sediment Retention Method= 0
XS Weighting Method= 0
Number of US Weighted Cross Sections= 1
Number of DS Weighted Cross Sections= 1
Upstream XS Weight=0
Main XS Weight=1
Downstream XS Weight=0
Number of DS XS's Weighted with US Boundary= 1
Upstream Boundary Weight= 1
Weight of XSs Associated with US Boundary= 0
Number of US XS's Weighted with DS Boundary= 1
Downstream Boundary Weight= 0.5
Weight of XSs Associated with DS Boundary= 0.5
Percentile Method= 0
Sediment Output Level= 3
Mass or Volume Output= 0
Output Increment Type= 1
Profile and TS Output Increment= 1
XS Output Flag= 0
XS Output Increment= 10
Write Gradation File= 0
Read Gradation Hotstart= 0
Write HDF5 File= 1
Write Binary Output= 1
Write DSS Sediment File= 0
SV Curve= 0
Specific Gage Flag= 0

--- BUFFALOCK.f01 (steady flow) ---

Flow Title=H2c
Program Version=5.07
Number of Profiles= 6
Profile Names=f1p,f10p,f4p,f2p,f02p,f1pplus
River Rch & RM=BUFFALOCK,Main            ,19930
     678     361     478     575     944    1000
River Rch & RM=BUFFALOCK,Main            ,18129
     790     423     559     671    1100    1170
River Rch & RM=BUFFALOCK,Main            ,16200
     899     483     637     764    1240    1330
River Rch & RM=BUFFALOCK,Main            ,10170
    1040     565     743     889    1440    1550
River Rch & RM=BUFFALOCK,Main            ,6795
    1190     647     849    1010    1640    1760
Boundary for River Rch & Prof#=BUFFALOCK,Main            , 1
Up Type= 0
Dn Type= 3
Dn Slope=0.00096
Boundary for River Rch & Prof#=BUFFALOCK,Main            , 2
Up Type= 0
Dn Type= 3
Dn Slope=0.00096
Boundary for River Rch & Prof#=BUFFALOCK,Main            , 3
Up Type= 0
Dn Type= 3
Dn Slope=0.00096
Boundary for River Rch & Prof#=BUFFALOCK,Main            , 4
Up Type= 0
Dn Type= 3
Dn Slope=0.00096
Boundary for River Rch & Prof#=BUFFALOCK,Main            , 5
Up Type= 0
Dn Type= 3
Dn Slope=0.00096
Boundary for River Rch & Prof#=BUFFALOCK,Main            , 6
Up Type= 0
Dn Type= 3
Dn Slope=0.00096
DSS Import GetInterval= 0
DSS Import GetPeak= 0
DSS Import FillOption= 0

--- BUFFALOCK.g01 (geometry) ---

Geom Title=H2c
Program Version=5.07

River Reach=BUFFALOCK       ,Main
Reach XY= 30
     2036781.121      315147.054     2037460.204      314513.221
     2038837.078      314317.675 2040353.0948371314664.442789481
     2040613.954      314484.0032040909.37682763314551.119934691
     2040897.748      314426.319      2041220.28      314648.189
     2042351.151      314112.583     2042568.432      314318.558
     2043543.787      314330.558     2043690.729      314571.064
     2043804.671       314433.82     2044341.701      314701.488
     2044453.735      314506.538     2045104.157      314448.106
     2045224.784      314179.369     2045546.818      314234.264
     2046156.091       313707.93     2046216.622      313886.405
2046916.36211902313855.195376396     2047009.411      313676.082
     2047373.445      313828.555     2047457.999      313655.418
     2047979.718      313459.597     2048202.857      313047.441
2049054.84359817312859.140401331     2049986.581      312072.471
     2050742.875      312217.871     2050722.828      312577.749

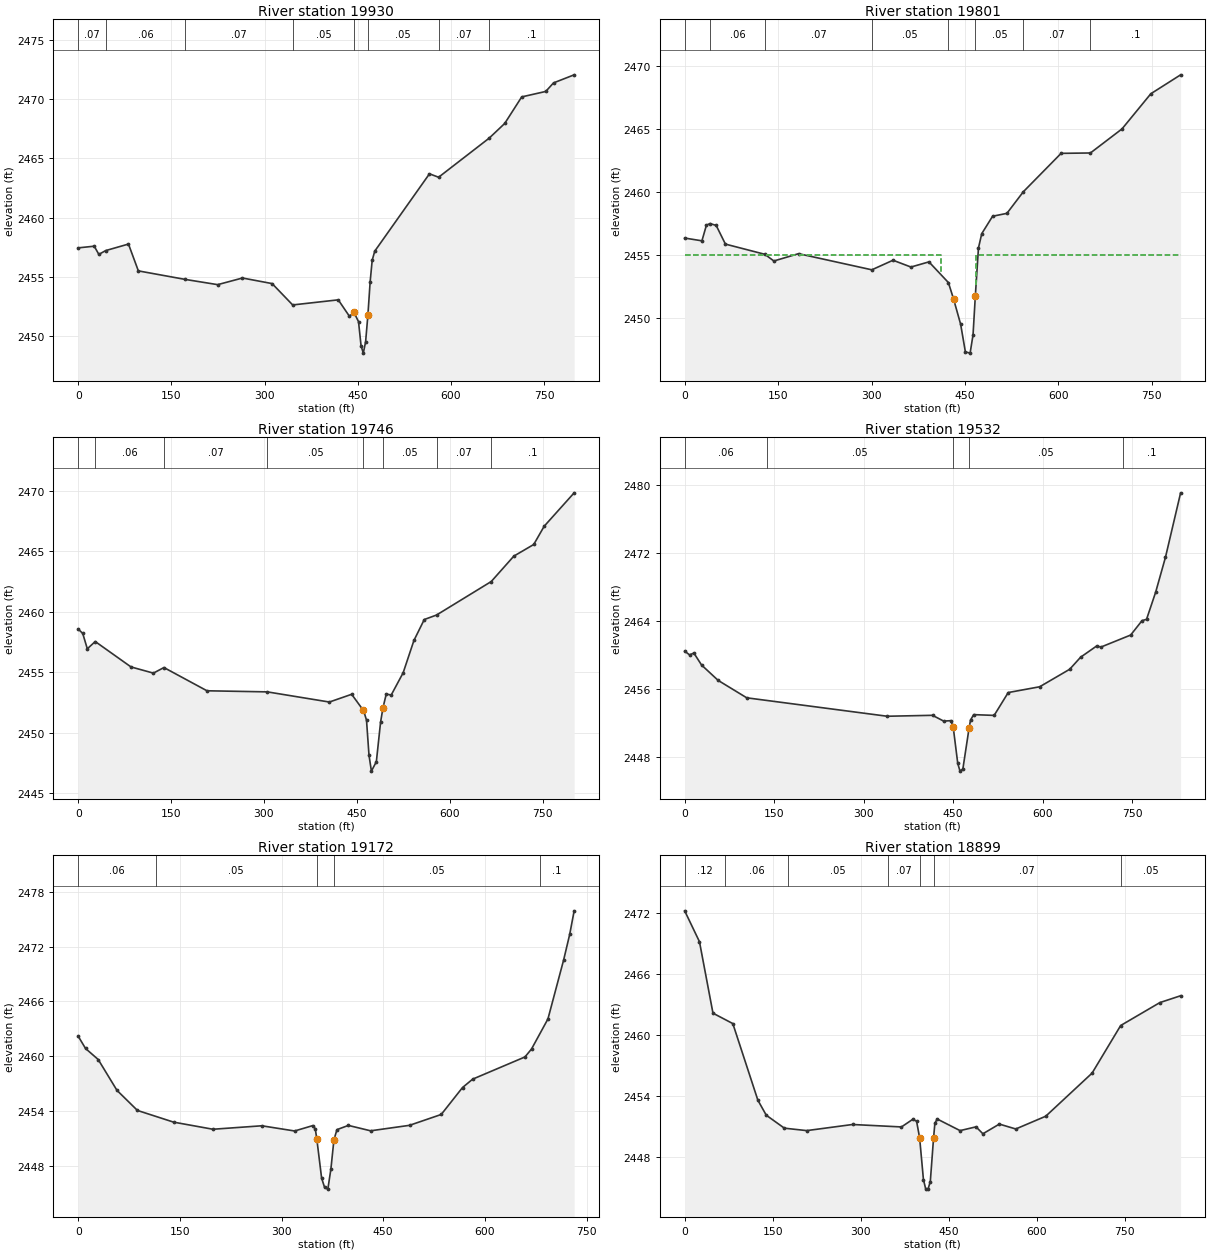
Type RM Length L Ch R = 1 ,19930   ,140.2,128.6,124
XS GIS Cut Line= 2
 2037005.2085702315550.7273786532036647.31441755 314837.13026205
#Sta/Elev= 30
       0 2457.45    25.8 2457.59    33.2  2456.9    44.2 2457.22    80.9 2457.77
    96.8 2455.51   172.4 2454.79   224.5 2454.35   264.4 2454.91   312.1 2454.44
   345.2 2452.64   418.6 2453.07   436.5 2451.69   443.9 2452.01   451.2 2451.23
   455.3  2449.2   458.9 2448.58   462.6 2449.53   466.3 2451.78   469.9 2454.58
   473.2  2456.4   477.3 2457.17   565.4 2463.69   580.1  2463.4   661.4 2466.69
   686.5 2467.93   713.9 2470.17   752.6 2470.63   765.1 2471.35   798.3 2472.03
#Mann= 8 ,-1 , 0
       0     .07       0    44.2     .06       0   172.4     .07       0
   345.2     .05       0   443.9    .045       0   466.3     .05       0
   580.1     .07       0   661.4      .1       0
Bank Sta=443.9,466.3
XS Rating Curve= 0 ,0
Exp/Cntr(USF)=0,0
Exp/Cntr=0.5,0.3

Type RM Length L Ch R = 1 ,19801   ,54.4,55.5,56.9
XS GIS Cut Line= 4
2037104.34971693315477.3437734612036924.20202207315084.294257396
2036871.79541993315054.8155436912036742.96252299314779.680882446
#Sta/Elev= 30
       0 2456.38    27.7 2456.16    34.9  2457.4    40.7 2457.53    50.6 2457.38
    65.4  2455.9   128.7 2455.09   143.2 2454.56   182.9 2455.14   300.5 2453.86
   334.5 2454.62   363.3 2454.08   392.2 2454.49   423.4 2452.85   431.7 2451.55
   443.1 2449.54   450.7 2447.35   458.3 2447.25     463  2448.7   466.7  2451.8
   471.7 2455.59     477 2456.73   494.4 2458.11   517.4 2458.34   543.7 2460.05
   604.4  2463.1   651.5 2463.13   702.2 2465.04   748.5 2467.83   796.3 2469.33
#Mann= 8 ,-1 , 0
       0     .07       0    40.7     .06       0   128.7     .07       0
   300.5     .05       0   423.4    .045       0   466.7     .05       0
   543.7     .07       0   651.5      .1       0
#XS Ineff= 2 , 0
          411.26    2455  467.81            2455
Permanent Ineff=
       F       F
Bank Sta=431.7,466.7
XS Rating Curve= 0 ,0
Exp/Cntr(USF)=0,0
Exp/Cntr=0.5,0.3

Type RM Length L Ch R = 1 ,19746   ,206.3,213.8,218.9
XS GIS Cut Line= 4
2037152.08809181315441.122295308   2036975.51682315055.907347903
2036904.54954626315006.7761583952036789.91010408314739.284126629
#Sta/Elev= 30
       0 2458.55     7.3 2458.19    14.7 2456.92    27.5 2457.52    85.3 2455.42
   121.4 2454.91   138.5 2455.37     208 2453.45   305.4 2453.36   405.7 2452.52
   441.7 2453.16   460.62451.832   460.8 2451.84   465.7 2451.02   469.7 2448.13
   473.6 2446.81   481.6 2447.59   488.4 2450.85   492.3 2452.05   497.6 2453.18
   505.6  2453.1   524.9 2454.94   542.3 2457.61     559 2459.34   578.8 2459.71
   667.2 2462.48   703.7 2464.58   735.8 2465.54   752.7 2467.05   801.1 2469.81
#Mann= 8 ,-1 , 0
       0     .07       0    27.5     .06       0   138.5     .07       0
   305.4     .05       0   460.8    .045       0   492.3     .05       0
   578.8     .07       0   667.2      .1       0
Bank Sta=460.6,492.3
XS Rating Curve= 0 ,0
Exp/Cntr(USF)=0,0
Exp/Cntr=0.5,0.3

Type RM Length L Ch R = 1 ,19532   ,361.2,359.9,354.5
XS GIS Cut Line= 2
2037326.21059187315304.6114216382036902.85960729 314589.46148265
#Sta/Elev= 30
       0 2460.48     8.2 2460.03    15.4 2460.25    28.3 2458.84    56.1 2457.03
     104 2454.98   339.4 2452.81   415.3 2452.92     434 2452.24   446.2 2452.29
     450 2451.54   457.6 2447.27   461.4 2446.35   466.2 2446.61   476.7 2451.46
   479.1 2452.37   484.3    2453   518.6 2452.91   542.2  2455.6   594.9 2456.28
   645.2 2458.34   663.5 2459.76   690.2 2461.07   697.8 2460.96   747.4 2462.37
   766.4 2464.06     774 2464.22   789.3 2467.42   805.7 2471.52   831.1 2479.11
#Mann= 5 ,-1 , 0
       0     .06       0  137.24     .05       0     450    .045       0
   476.7     .05       0  734.12      .1       0
Bank Sta=450,476.7
XS Rating Curve= 0 ,0
Exp/Cntr(USF)=0,0
Exp/Cntr=0.3,0.1

Type RM Length L Ch R = 1 ,19172   ,270.7,272.8,276.3
XS GIS Cut Line= 2
2037605.81631162314927.3584821172037067.44125057314431.875939665
#Sta/Elev= 30
       0 2462.19    10.8 2460.85    29.5 2459.64    57.2 2456.26    87.4 2454.06
   140.7 2452.78   198.8    2452   270.9 2452.38   319.3 2451.81   346.1  2452.4
   349.8 2452.04   352.1 2450.89   359.1 2446.65   363.5 2445.63   368.3 2445.44
   372.8 2447.63   377.3 2450.86   381.8 2451.96   398.6 2452.42   431.4 2451.83
   488.8 2452.43   535.6 2453.62     567 2456.57     582 2457.49   659.1 2459.92
   668.8 2460.79     693 2464.08   716.2 2470.55   725.1 2473.34   731.7 2475.93
#Mann= 5 ,-1 , 0
       0     .06       0  114.07     .05       0   352.1    .045       0
   377.3     .05       0  681.34      .1       0
Bank Sta=352.1,377.3
XS Rating Curve= 0 ,0
Exp/Cntr(USF)=0,0
Exp/Cntr=0.3,0.1

Type RM Length L Ch R = 1 ,18899   ,444.7,445.9,446.7
XS GIS Cut Line= 2
2037738.80320518314843.1255369052037282.94465819314131.902208049
#Sta/Elev= 30
       0 2472.18    25.2 2469.15    48.2 2462.14      82 2461.12   124.7  2453.6
     139 2452.13   169.8 2450.86   207.9 2450.62   285.9 2451.22   369.3 2450.98
   388.3 2451.72     395 2451.55   400.2 2449.92   406.7 2445.82   410.6 2444.89
   414.5 2444.88   418.4 2445.61   423.9 2449.86   426.2 2451.34   430.1 2451.76
   469.1 2450.62   496.3 2450.99     508 2450.31     536 2451.26     564 2450.78
     615 2452.03     694 2456.26   742.7 2460.93   809.5 2463.18   844.8 2463.85
#Mann= 7 ,-1 , 0
       0     .12       0   68.81     .06       0  175.54     .05       0
  346.18     .07       0   400.2    .045       0   423.9     .07       0
  742.59     .05       0
Bank Sta=400.2,423.9
XS Rating Curve= 0 ,0
Exp/Cntr(USF)=0,0
Exp/Cntr=0.3,0.1

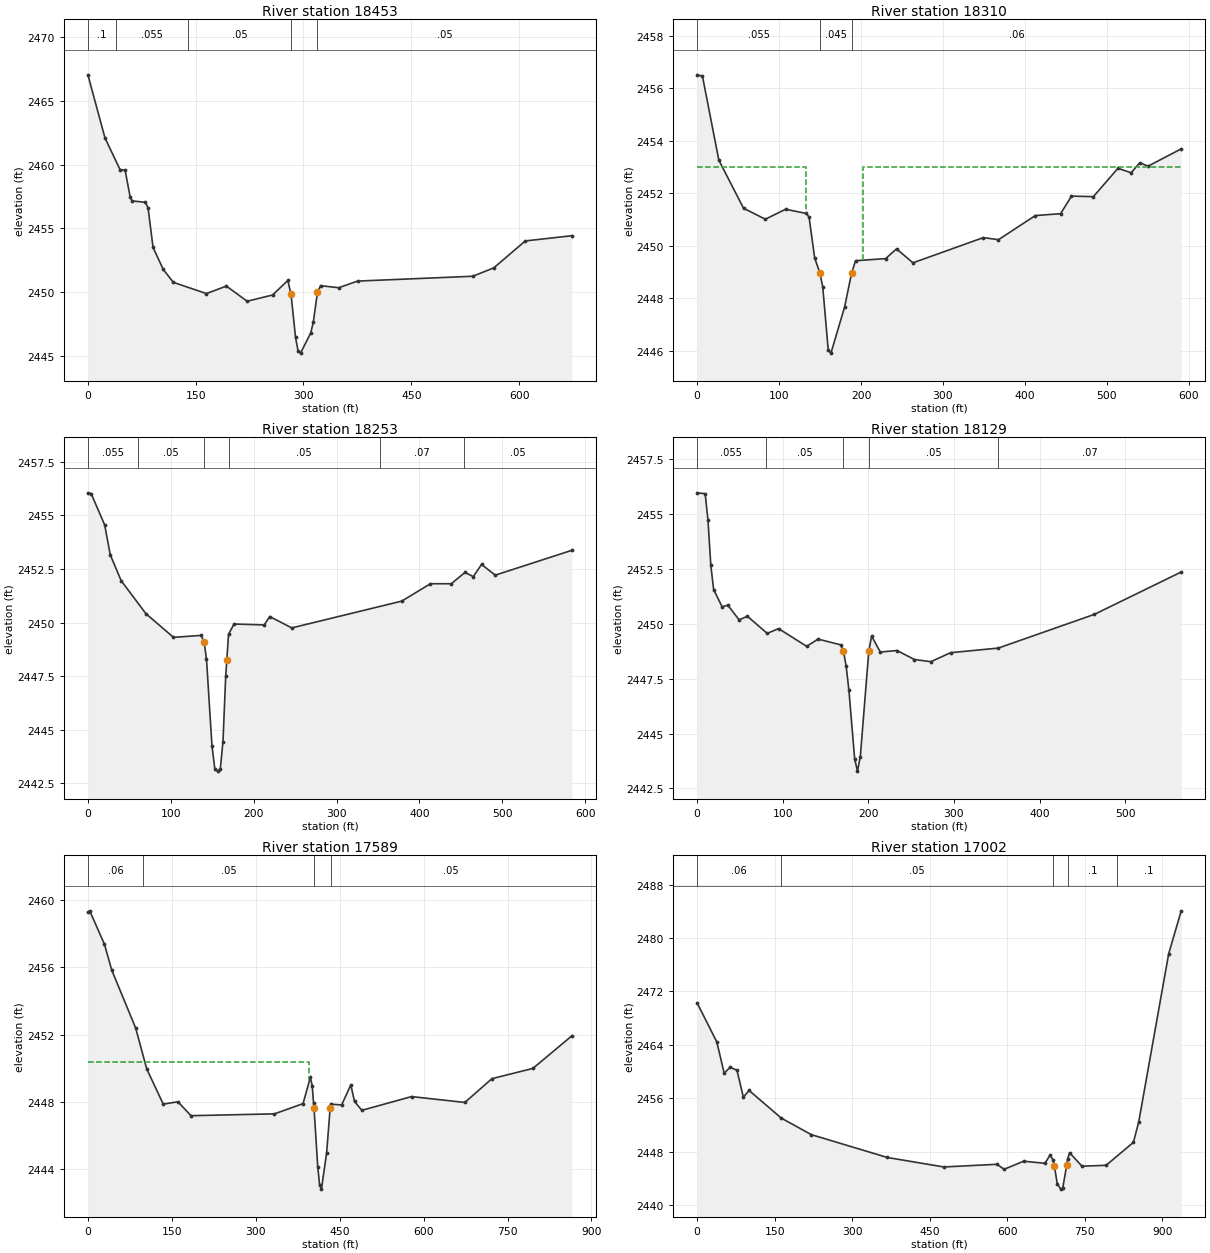
Type RM Length L Ch R = 1 ,18453   ,141.3,143.4,147.3
XS GIS Cut Line= 2
2038055.88045177 314670.175440322037803.85157208314045.629145059
#Sta/Elev= 30
       0 2467.04    23.8 2462.09    44.7 2459.61    51.8 2459.56    58.9 2457.44
    61.6 2457.15    80.1 2457.04    83.7 2456.61    90.7  2453.5   104.9 2451.77
     119 2450.76     165 2449.88   192.7 2450.47   221.6 2449.28     257 2449.77
   278.2 2450.91   282.72449.811   288.9 2446.45   292.4  2445.4   295.9 2445.21
   310.1  2446.8   313.7 2447.66   319.4 2449.97   323.8  2450.5     349 2450.34
   375.2 2450.86   535.5 2451.24   564.8  2451.9   608.6 2454.01   673.5 2454.42
#Mann= 5 ,-1 , 0
       0      .1       0   39.49    .055       0  139.61     .05       0
   282.7    .045       0   319.4     .05       0
Bank Sta=282.7,319.4
XS Rating Curve= 0 ,0
Exp/Cntr(USF)=0,0
Exp/Cntr=0.5,0.3

Type RM Length L Ch R = 1 ,18310   ,56.8,57.2,61.1
XS GIS Cut Line= 2
2038115.39916236314582.5991063652038008.77427733314001.553384567
#Sta/Elev= 30
       0 2456.51     6.5 2456.46    26.5 2453.26    56.6 2451.43    83.2 2451.01
   107.9 2451.39   133.3 2451.23   136.6 2451.09   143.4 2449.54   149.9 2448.95
   153.3 2448.43     160 2446.02   163.3 2445.91     180 2447.67   188.5 2448.96
   193.3 2449.43     230 2449.51   243.3 2449.88   263.4 2449.35   349.2 2450.31
   367.7 2450.23   412.7 2451.15   443.5 2451.22   456.8 2451.89   483.5 2451.87
   513.5 2452.95   529.6 2452.78   540.2 2453.16   550.2 2453.03   590.7 2453.69
#Mann= 3 ,-1 , 0
       0    .055       0   149.9    .045       0   188.5     .06       0
#XS Ineff= 2 , 0
          132.97    2453  202.01            2453
Permanent Ineff=
       F       F
Bank Sta=149.9,188.5
XS Rating Curve= 0 ,0
Exp/Cntr(USF)=0,0
Exp/Cntr=0.5,0.3

Type RM Length L Ch R = 1 ,18253   ,122.1,123.3,124.2
XS GIS Cut Line= 2
2038165.71652383314576.6089442852038078.26015746313999.157319735
#Sta/Elev= 30
       0 2456.05       4 2456.01    20.3 2454.55      27 2453.16    40.2 2451.95
    70.1 2450.41   103.3 2449.31   136.6  2449.4   140.2  2449.1   143.1  2448.3
   149.7 2444.26   153.1 2443.19   156.4 2443.07   159.7 2443.15     163 2444.45
   166.3 2447.51   167.62448.252   169.7 2449.45   176.3 2449.93   212.8 2449.89
   219.4 2450.28     246 2449.75   378.7    2451   413.3 2451.81   438.4 2451.81
     455 2452.34     465 2452.14   474.9 2452.71   491.5 2452.21     584 2453.37
#Mann= 6 ,-1 , 0
       0    .055       0   60.45     .05       0   140.2    .045       0
   169.7     .05       0   352.3     .07       0  453.17     .05       0
Bank Sta=140.2,167.6
XS Rating Curve= 0 ,0
Exp/Cntr(USF)=0,0
Exp/Cntr=0.5,0.3

Type RM Length L Ch R = 1 ,18129   ,540.2,540.4,540.9
XS GIS Cut Line= 2
2038275.93550611314579.0050091172038224.42011222 314015.92977356
#Sta/Elev= 30
       0 2455.98     9.4 2455.94    12.7 2454.72      16 2452.67    19.3 2451.57
    29.2 2450.78    35.8 2450.86      49 2450.19    58.8 2450.35    81.9 2449.57
    95.1 2449.79     128 2448.98   141.2 2449.31   167.6 2449.05   170.8 2448.79
   174.1 2448.07   177.3 2446.97     184 2443.85   187.3 2443.29   190.6 2443.95
   200.5 2448.76   203.8 2449.45   213.9 2448.72   233.4 2448.79   253.8 2448.38
     273 2448.28     296 2448.69   351.7  2448.9   464.1 2450.44   565.4 2452.37
#Mann= 5 ,-1 , 0
       0    .055       0   79.97     .05       0   170.8    .045       0
   200.5     .05       0  351.53     .07       0
Bank Sta=170.8,200.5
XS Rating Curve= 0 ,0
Exp/Cntr(USF)=0,0
Exp/Cntr=0.3,0.1

Type RM Length L Ch R = 1 ,17589   ,582.8,586.5,592.6
XS GIS Cut Line= 2
2038815.29607196314736.9570689352038765.99432644313873.263527089
#Sta/Elev= 30
       0 2459.29     3.3 2459.38    29.6 2457.39    42.7 2455.84    85.4 2452.39
   105.2 2449.95   134.7 2447.85     161 2447.99   184.3 2447.16   333.5 2447.27
   384.5 2447.88   397.6 2449.44   400.9 2448.96   403.3 2447.93   404.2 2447.59
   410.8 2444.12   414.1 2443.04   417.4 2442.78   426.7 2444.95     433 2447.63
   433.8 2447.85   453.5  2447.8   469.9    2449   476.5 2448.01   489.6 2447.48
   578.4  2448.3   673.7 2447.95   722.1 2449.37   795.3 2449.98   865.1 2451.93
#Mann= 4 ,-1 , 0
       0     .06       0   99.23     .05       0   403.3    .045       0
   433.8     .05       0
#XS Ineff= 2 , 0
          396.02 2450.38
Permanent Ineff=
       F       F
Bank Sta=404.2,433
XS Rating Curve= 0 ,0
Exp/Cntr(USF)=0,0
Exp/Cntr=0.3,0.1

Type RM Length L Ch R = 1 ,17002   ,349.1,349.1,348.6
XS GIS Cut Line= 3
 2039036.2409315314999.8997116962039215.18800783314910.426173535
2039428.82890507314205.593811689
#Sta/Elev= 30
       0 2470.27    38.1 2464.42    52.4 2459.73    63.8 2460.64    77.1 2460.18
    89.5 2456.14   100.5 2457.16   162.8 2453.02   220.9 2450.54     368 2447.12
   477.3  2445.7   580.2  2446.1     594 2445.35   631.6 2446.56   672.9 2446.25
     683 2447.48   688.7 2446.73   691.3 2445.82   696.7  2443.2   703.6 2442.38
   707.3 2442.51     715 2445.93   716.7 2446.84   720.7 2447.82   744.7 2445.81
   791.3 2445.95   844.2 2449.39   854.5 2452.49   912.3 2477.61   936.6 2484.06
#Mann= 5 ,-1 , 0
       0     .06       0  162.67     .05       0   688.7    .045       0
   716.7      .1       0  812.83      .1       0
Bank Sta=691.3,715
XS Rating Curve= 0 ,0
Exp/Cntr(USF)=0,0
Exp/Cntr=0.3,0.1

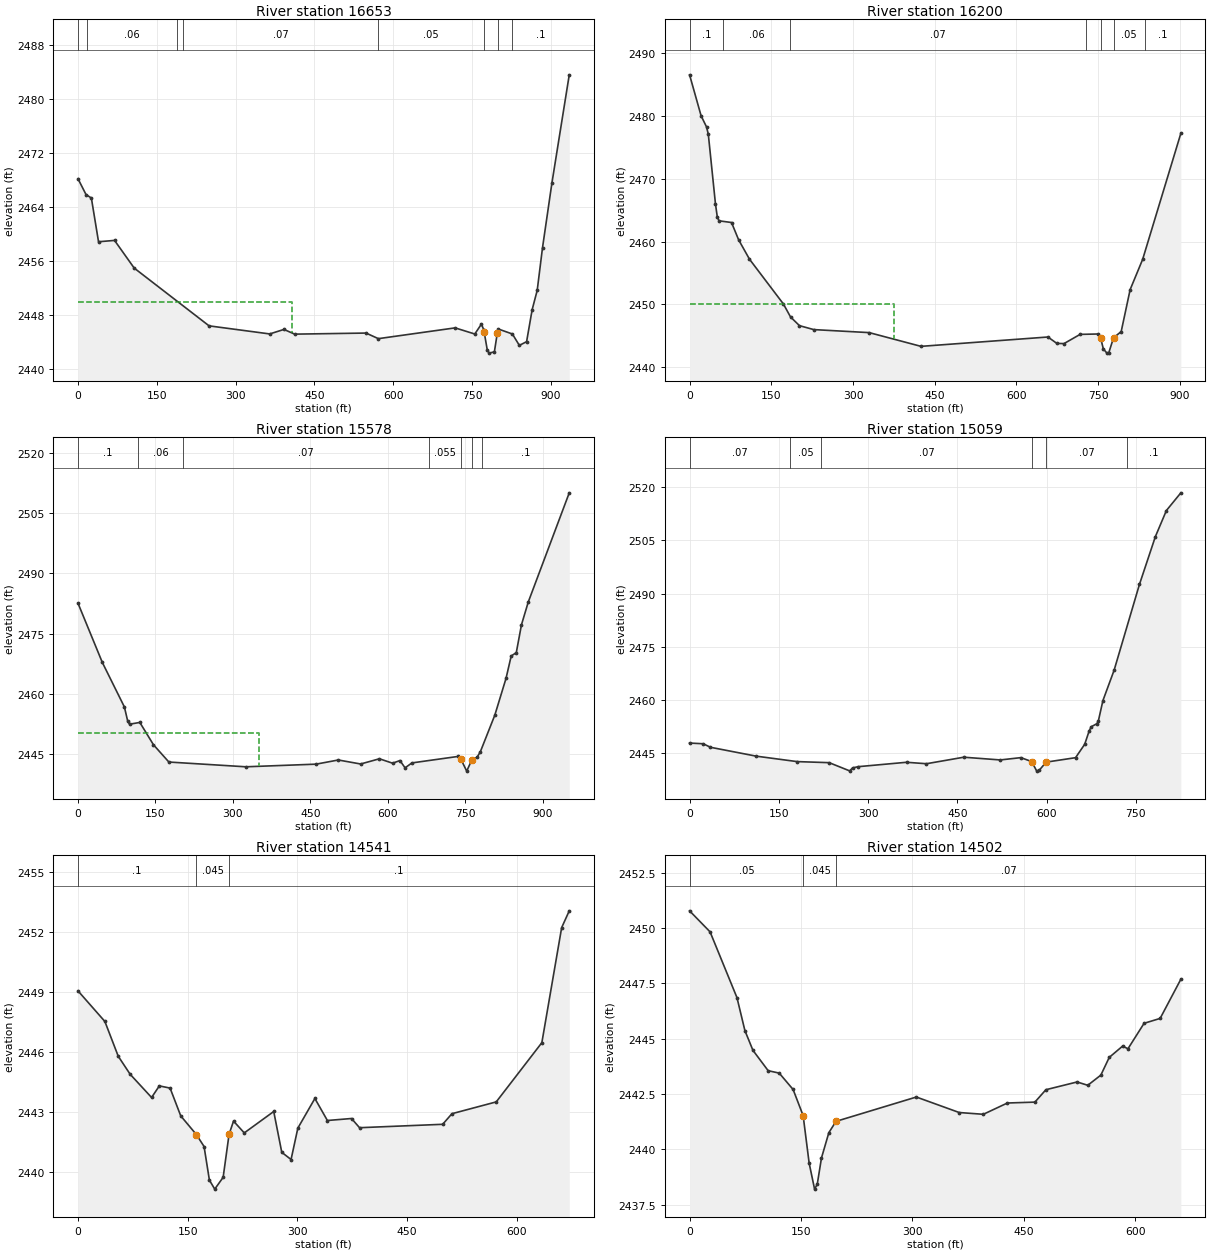
Type RM Length L Ch R = 1 ,16653   ,454.7,453.7,449.5
XS GIS Cut Line= 2
2039498.21654691315270.146316756 2039737.4213122314366.280982265
#Sta/Elev= 30
       0 2468.19    15.3 2465.84    25.5 2465.32    39.1 2458.83    69.6 2459.03
     107 2454.92   249.5 2446.34   364.9 2445.14     392 2445.81   412.4 2445.11
   548.2 2445.27   571.7 2444.44   717.8 2446.04   755.2 2445.13   767.8  2446.6
   772.1 2445.79   773.1  2445.4   778.9 2442.79   782.3 2442.29   792.5 2442.48
   798.2 2445.34   799.3 2445.89   826.8 2445.13     840 2443.44   853.8 2443.99
   864.4 2448.75     874 2451.61   884.1 2457.95   901.9 2467.51     935 2483.62
#Mann= 8 ,-1 , 0
       0     .05       0    16.5     .06       0  189.28     .05       0
  199.81     .07       0  570.58     .05       0   772.1    .045       0
   799.3     .05       0   825.6      .1       0
#XS Ineff= 2 , 0
          407.38  2449.9
Permanent Ineff=
       F       F
Bank Sta=773.1,798.2
XS Rating Curve= 0 ,0
Exp/Cntr(USF)=0,0
Exp/Cntr=0.3,0.1

Type RM Length L Ch R = 1 ,16200   ,597.7,621.3,594.7
XS GIS Cut Line= 2
2040131.44703418315338.8927328252040144.97289029314437.168992218
#Sta/Elev= 30
       0 2486.58    21.2 2480.04    31.1 2478.28    34.4 2477.11    47.5 2466.02
    50.8 2463.98      54 2463.31      77 2463.04    90.1 2460.27     110 2457.19
   172.2 2450.06   185.3 2447.99   201.7  2446.6     228 2445.97   329.7 2445.49
   424.8  2443.3   657.8 2444.79   674.2 2443.77   687.3 2443.74   716.9 2445.21
   750.1 2445.27   754.72444.582   759.5  2442.9   766.1 2442.22   769.4 2442.25
   778.22444.658   792.3 2445.66   808.7 2452.34   831.7 2457.17   901.8 2477.25
#Mann= 7 ,-1 , 0
       0      .1       0   61.81     .06       0  183.94     .07       0
  727.19     .05       0  754.67    .045       0  778.17     .05       0
  836.05      .1       0
#XS Ineff= 2 , 0
          374.91 2450.07
Permanent Ineff=
       F       F
Bank Sta=754.7,778.2
XS Rating Curve= 0 ,0
Exp/Cntr(USF)=0,0
Exp/Cntr=0.3,0.1

Type RM Length L Ch R = 1 ,15578   ,505,519.6,487.8
XS GIS Cut Line= 2
2040731.09332168315226.1772652492040593.27965874314284.432703095
#Sta/Elev= 30
       0 2482.57    47.2 2467.77    89.9 2456.68    96.5 2453.05    99.9 2452.37
   119.8 2452.81   146.3 2447.23   176.1 2442.93   325.3 2441.74   461.3  2442.4
   504.4 2443.44   547.6 2442.44     584 2443.74   609.5 2442.64   623.8  2443.3
   633.7 2441.48     647 2442.71   736.5 2444.33   741.4 2443.77   753.1 2440.66
     763 2443.45     773 2444.07   779.6 2445.51   807.6 2454.64   829.3 2463.81
   839.3 2469.39   849.2 2470.24   859.2 2477.18   872.4 2482.87   951.8 2510.11
#Mann= 7 ,-1 , 0
       0      .1       0  116.72     .06       0  202.66     .07       0
  680.56    .055       0   741.4    .045       0     763    .055       0
   783.2      .1       0
#XS Ineff= 2 , 0
          350.55 2450.23
Permanent Ineff=
       F       F
Bank Sta=741.4,763
XS Rating Curve= 0 ,0
Exp/Cntr(USF)=0,0
Exp/Cntr=0.3,0.1

Type RM Length L Ch R = 1 ,15059   ,517.5,517.5,517.5
XS GIS Cut Line= 2
2041174.85370823 314931.197565842040747.38583253314224.633544092
#Sta/Elev= 30
       0 2447.77    23.1 2447.57      35 2446.58     112 2444.07   180.8 2442.53
   234.7 2442.23   269.1 2439.91     274 2440.75   283.5  2441.1   364.7 2442.34
   398.2 2441.93   460.9 2443.77   522.3    2443   556.8 2443.65     575 2442.55
   583.6 2439.84   587.5 2440.04   599.4 2442.38   648.8 2443.64   664.2 2447.43
   671.8 2451.26   675.3 2452.39   684.9 2453.26   687.2 2454.06   694.8 2459.77
   713.6 2468.34   756.2 2492.59     783  2506.1   801.5 2513.46   825.8 2518.46
#Mann= 6 ,-1 , 0
       0     .07       0  168.43     .05       0   221.1     .07       0
     575    .045       0   599.4     .07       0   734.5      .1       0
Bank Sta=575,599.4
XS Rating Curve= 0 ,0
Exp/Cntr(USF)=0,0
Exp/Cntr=0.5,0.3

Type RM Length L Ch R = 1 ,14541   ,39.1,39.1,39.1
XS GIS Cut Line= 2
2041282.14016234314812.4903250192040981.69452487314211.265327377
#Sta/Elev= 30
       0 2449.06    36.8 2447.53    55.1 2445.79    71.4 2444.89   100.7 2443.73
   111.3 2444.31     126  2444.2   140.6 2442.81   161.9 2441.88   172.5 2441.28
   179.8  2439.6   187.1 2439.15   198.6 2439.74   206.7 2441.89   212.8 2442.55
   227.5 2441.96   267.8 2443.03   278.8 2440.99   291.5 2440.63   300.8  2442.2
   324.1 2443.68   341.2 2442.58   374.2 2442.68   385.2 2442.22   498.9 2442.39
   511.6 2442.92   572.2 2443.51   634.6 2446.47   661.7 2452.22   672.1 2453.06
#Mann= 3 , 0 , 0
       0      .1       0   161.9    .045       0   206.7      .1       0
#XS Ineff= 2 , 0
          154.05    2442  209.19            2442
Permanent Ineff=
       F       F
Bank Sta=161.9,206.7
XS Rating Curve= 0 ,0
Exp/Cntr(USF)=0,0
Exp/Cntr=0.5,0.3

Type RM Length L Ch R = 1 ,14502   ,169.5,187.5,153.3
XS GIS Cut Line= 2
2041308.11085387314798.1560660342041033.48588313314196.504186679
#Sta/Elev= 30
       0 2450.78    27.6 2449.83    63.8 2446.86    74.5 2445.37    85.3 2444.48
   105.8 2443.56   120.7 2443.45   139.4 2442.71   152.9 2441.53     161 2439.38
   168.3 2438.21   171.9 2438.43   177.6 2439.62   187.5 2440.76   197.1 2441.27
   305.3 2442.37     363 2441.67   395.5 2441.59   427.9  2442.1   464.9 2442.14
   479.7  2442.7   521.7 2443.05   536.1  2442.9   553.7 2443.36     565 2444.16
     583 2444.67   590.2 2444.55   611.9  2445.7   633.5 2445.92   661.4 2447.69
#Mann= 3 ,-1 , 0
       0     .05       0   152.9    .045       0   197.1     .07       0
Bank Sta=152.9,197.1
XS Rating Curve= 0 ,0
Exp/Cntr(USF)=0,0
Exp/Cntr=0.5,0.3

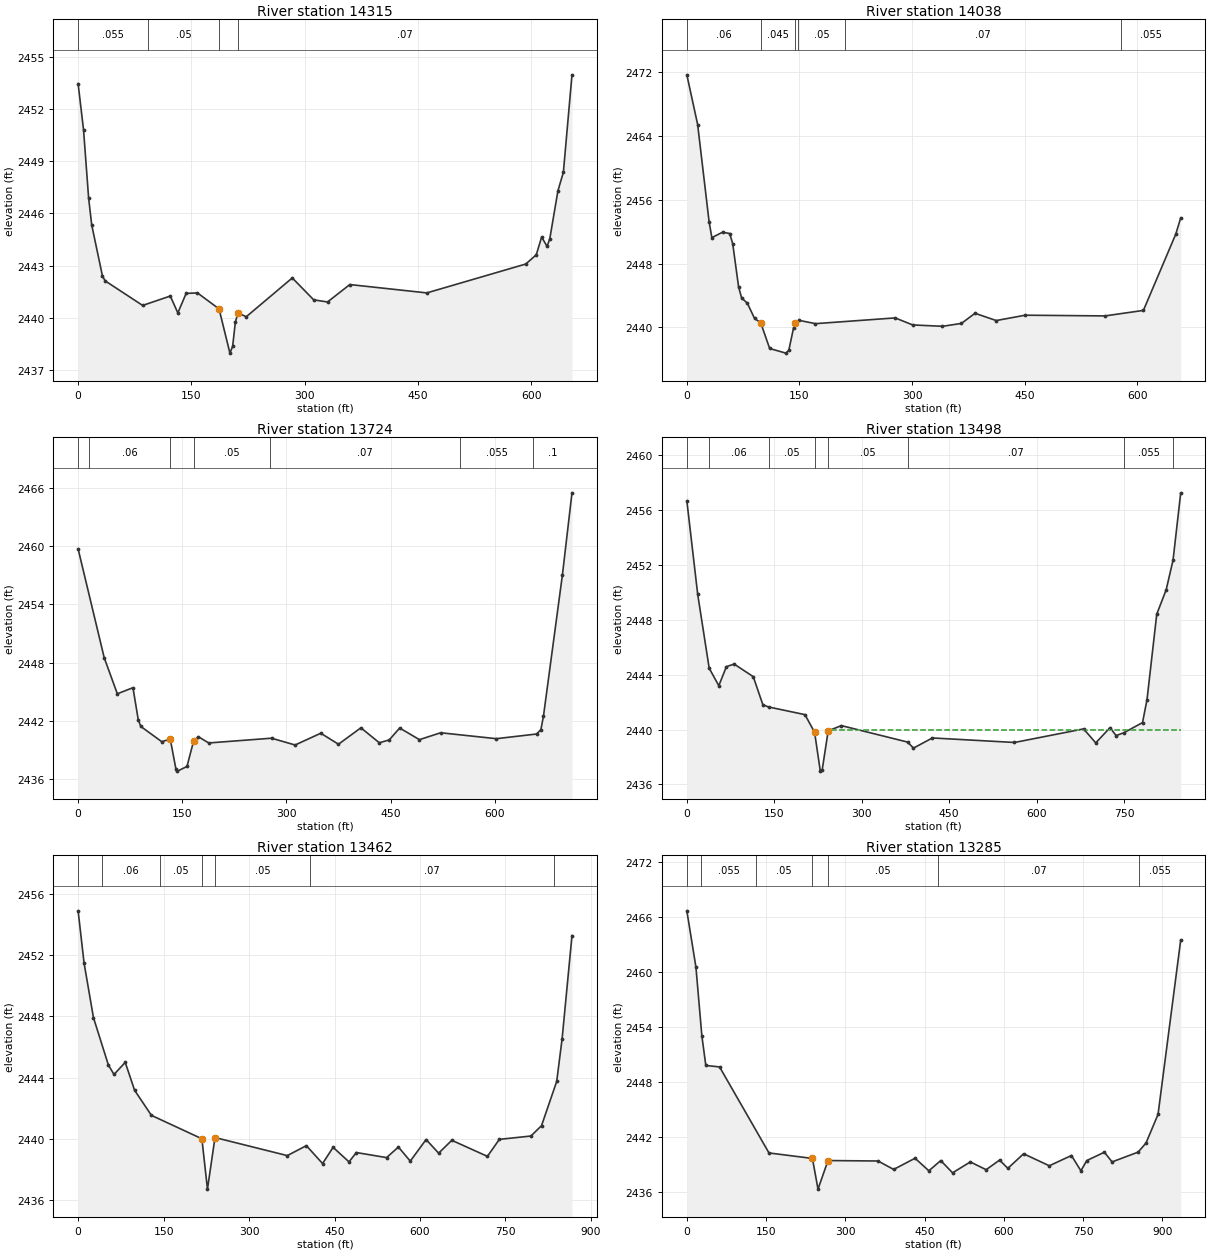
Type RM Length L Ch R = 1 ,14315   ,273,276.6,259.1
XS GIS Cut Line= 2
2041398.35863577314694.3225965332041132.46732135314096.552342206
#Sta/Elev= 30
       0 2453.45     7.2  2450.8    13.9 2446.89      18 2445.34    32.3 2442.39
    35.9 2442.12    85.5 2440.71   122.1 2441.25   132.1 2440.28   143.1  2441.4
   158.1 2441.43   186.7 2440.51   201.1 2437.97   204.7 2438.36   208.3 2439.76
   211.9 2440.28   222.7 2440.06   283.7 2442.29   312.1 2441.03   330.4 2440.91
   359.9 2441.91   461.9 2441.43     593 2443.09   606.9 2443.62     614 2444.64
   621.2  2444.1   624.8 2444.54   635.6  2447.3   642.8 2448.36   654.2 2453.96
#Mann= 4 ,-1 , 0
       0    .055       0    93.1     .05       0   186.7    .045       0
   211.9     .07       0
Bank Sta=186.7,211.9
XS Rating Curve= 0 ,0
Exp/Cntr(USF)=0,0
Exp/Cntr=0.3,0.1

Type RM Length L Ch R = 1 ,14038   ,285.7,314.5,296.2
XS GIS Cut Line= 2
2041614.84051626314607.4117650482041251.49651214314059.067891051
#Sta/Elev= 30
       0 2471.64    14.4 2465.41    29.6 2453.27    33.3 2451.25    47.5 2451.93
    57.1 2451.77    61.1 2450.49    68.9  2445.1    72.9 2443.72    80.7 2443.02
    90.2 2441.13    98.4 2440.59   110.3 2437.37   131.9 2436.79   135.8 2437.14
   142.2 2439.98   144.6 2440.55   149.3  2440.9   171.3 2440.48   277.5  2441.2
   300.8 2440.32   340.5 2440.15   365.7 2440.51   383.8 2441.78   412.1 2440.87
   450.7 2441.54     557 2441.45   608.1 2442.14   651.2 2451.69   657.8 2453.73
#Mann= 6 ,-1 , 0
       0     .06       0    98.4    .045       0   144.6     .06       0
  148.42     .05       0   210.7     .07       0  577.63    .055       0
Bank Sta=98.4,144.6
XS Rating Curve= 0 ,0
Exp/Cntr(USF)=0,0
Exp/Cntr=0.3,0.1

Type RM Length L Ch R = 1 ,13724   ,211.8,225.1,221.8
XS GIS Cut Line= 2
2041839.65647582314563.0401940822041490.60011755313943.317252925
#Sta/Elev= 30
       0  2459.7    37.6 2448.49    56.5 2444.78      79 2445.41    86.6 2442.12
    90.3 2441.42   120.5 2439.85   132.7 2440.12     141 2436.99   143.1 2436.82
   156.8  2437.3   166.4 2439.93   173.2 2440.36   188.1 2439.72   278.6 2440.21
   312.5 2439.51   349.5 2440.72     375 2439.59   407.3 2441.28   433.8 2439.74
   448.1 2440.03   463.1 2441.26   491.6 2440.06   522.1 2440.77   602.3 2440.16
   660.2 2440.64   666.5 2441.09   670.2 2442.47   697.5 2457.01   711.3 2465.47
#Mann= 7 ,-1 , 0
       0      .1       0   15.59     .06       0   132.7    .045       0
   166.4     .05       0  276.52     .07       0  550.69    .055       0
  654.82      .1       0
Bank Sta=132.7,166.4
XS Rating Curve= 0 ,0
Exp/Cntr(USF)=0,0
Exp/Cntr=0.5,0.3

Type RM Length L Ch R = 1 ,13498   ,35.8,36.1,36.6
XS GIS Cut Line= 3
2041931.73878553314561.9880154572041914.44614603314246.790359113
2041734.44548942313746.875871744
#Sta/Elev= 30
       0 2456.69    18.6 2449.87    38.3 2444.48    54.8  2443.2    67.8 2444.59
    81.1 2444.78   113.9 2443.86   130.4 2441.81   140.2 2441.65   202.6 2441.09
   219.1  2439.8   228.9 2436.97   232.2 2437.08   242.4 2439.91   265.1 2440.29
   378.5 2439.09   388.7 2438.65   421.1 2439.39   561.9 2439.06   680.4 2440.05
   701.3 2439.03   725.7 2440.14   736.2 2439.56     750 2439.78   781.5 2440.51
   789.2 2442.19   805.9 2448.42     822 2450.19   833.8 2452.35     847 2457.27
#Mann= 8 ,-1 , 0
       0      .1       0    38.3     .06       0   140.2     .05       0
   219.1    .045       0   242.4     .05       0   378.5     .07       0
     750    .055       0   833.8      .1       0
#XS Ineff= 2 , 0
          212.08    2440   246.4            2440
Permanent Ineff=
       F       F
Bank Sta=219.1,242.4
XS Rating Curve= 0 ,0
Exp/Cntr(USF)=0,0
Exp/Cntr=0.5,0.3

Type RM Length L Ch R = 1 ,13462   ,180.8,176.9,168.6
XS GIS Cut Line= 3
2041959.24980292314560.4159573212041953.74759944 314243.64624284
2041773.74694283313724.081028766
#Sta/Elev= 30
       0  2454.9    10.5 2451.48    26.9 2447.93    53.1 2444.83      63 2444.21
    82.7    2445    99.1 2443.18   128.6 2441.54   217.2 2440.01     227 2436.72
   240.2 2440.09   367.1 2438.91   400.6 2439.56     429 2438.39   447.5 2439.45
   475.4  2438.5   488.3 2439.11   541.3 2438.78   562.1 2439.47   582.9 2438.55
   610.7 2439.96   632.7 2439.07   655.8 2439.91   718.3 2438.86   739.2 2439.97
   794.7 2440.19   813.3 2440.87   839.9 2443.76   849.4 2446.55   866.7 2453.28
#Mann= 7 ,-1 , 0
       0      .1       0   42.54     .06       0  142.87     .05       0
   217.2    .045       0   240.2     .05       0  406.33     .07       0
  835.36    .055       0
Bank Sta=217.2,240.2
XS Rating Curve= 0 ,0
Exp/Cntr(USF)=0,0
Exp/Cntr=0.5,0.3

Type RM Length L Ch R = 1 ,13285   ,204.8,205.4,203.6
XS GIS Cut Line= 2
2042233.08440505314499.4409423642041786.41059066313678.566879495
#Sta/Elev= 30
       0  2466.7    17.2 2460.55    28.4 2453.06    35.9 2449.82    61.9 2449.66
   155.4 2440.27   237.6 2439.67   248.2 2436.32   267.1 2439.44   361.9 2439.39
   391.3 2438.47   431.8 2439.69   457.9 2438.32   480.4 2439.44   502.8  2438.1
   536.4 2439.29   566.3 2438.44   591.7 2439.49   607.4 2438.59   637.2 2440.18
   685.8 2438.87   727.7 2439.99   745.6 2438.32   756.8 2439.44   790.1 2440.35
   804.6 2439.29   853.9 2440.36   868.8 2441.35   891.6 2444.48   934.5 2463.52
#Mann= 7 ,-1 , 0
       0      .1       0   27.57    .055       0  131.14     .05       0
   237.6    .045       0   267.1     .05       0  475.56     .07       0
  856.11    .055       0
Bank Sta=237.6,267.1
XS Rating Curve= 0 ,0
Exp/Cntr(USF)=0,0
Exp/Cntr=0.3,0.1

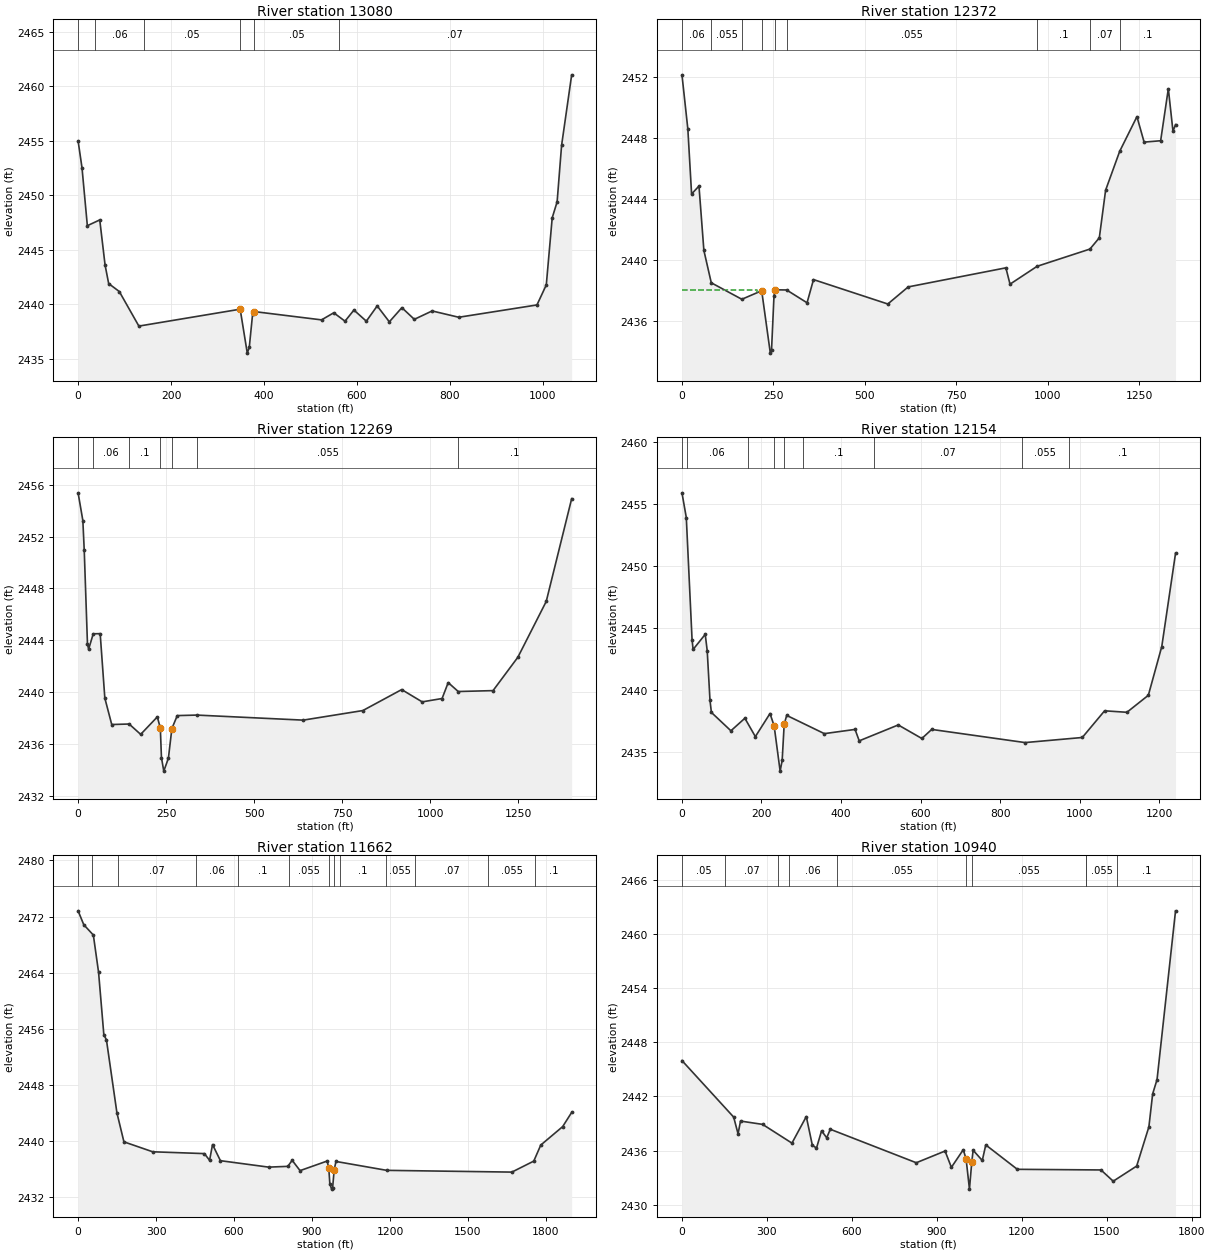
Type RM Length L Ch R = 1 ,13080   ,656.5,708.2,690.5
XS GIS Cut Line= 2
2042465.49958473 314471.835766572041919.52840288313560.666469778
#Sta/Elev= 30
       0 2454.98     8.4 2452.52    19.9  2447.2    46.6 2447.73    58.1 2443.58
    65.8 2441.89    88.7 2441.16   130.8 2437.99   348.8 2439.54   364.1 2435.51
   368.4 2436.04   375.6 2439.12   379.4 2439.32   523.9 2438.56   550.2 2439.21
   574.4 2438.44   593.6 2439.46   620.3 2438.44   643.7 2439.84   669.8 2438.38
   696.8 2439.68   723.6 2438.61   761.9 2439.38   819.2  2438.8   987.5 2439.93
  1007.6 2441.77  1020.3 2447.92  1030.9 2449.39  1040.5 2454.57  1062.2 2461.04
#Mann= 6 ,-1 , 0
       0      .1       0   37.23     .06       0  142.45     .05       0
   348.8    .045       0   379.4     .05       0  561.22     .07       0
Bank Sta=348.8,379.4
XS Rating Curve= 0 ,0
Exp/Cntr(USF)=0,0
Exp/Cntr=0.5,0.3

Type RM Length L Ch R = 1 ,12372   ,103.6,103.1,97.7
XS GIS Cut Line= 3
 2042620.1342815314480.4754195152042676.16480802314229.611963774
2041974.41999872313393.008122892
#Sta/Elev= 30
       0 2452.11    16.1 2448.55    26.3  2444.3    46.5 2444.82    59.9  2440.6
    80.1 2438.48   163.7  2437.4   217.9 2437.96   241.5 2433.87   244.8 2434.06
   251.5 2437.61   254.9 2438.02     286 2438.01   341.9 2437.17   359.5 2438.69
   562.6 2437.09   618.3 2438.21   885.3 2439.46   896.6 2438.39   970.6 2439.56
    1115 2440.69  1140.7 2441.43  1157.9 2444.55  1196.4  2447.1  1243.5 2449.37
  1263.1  2447.7  1308.3 2447.79  1329.3  2451.2    1342 2448.41    1349 2448.85
#Mann= 9 ,-1 , 0
       0     .06       0    80.1    .055       0   163.7      .1       0
   217.9    .045       0   254.9      .1       0     286    .055       0
   970.6      .1       0    1115     .07       0  1196.4      .1       0
#XS Ineff= 2 , 0
             205    2438     264            2438
Permanent Ineff=
       F       F
Bank Sta=217.9,254.9
XS Rating Curve= 0 ,0
Exp/Cntr(USF)=0,0
Exp/Cntr=0.5,0.3

Type RM Length L Ch R = 1 ,12269   ,110,114.9,121.3
XS GIS Cut Line= 3
2042767.60209436314520.7954364082042762.12757652314245.700914944
2042028.54218594313391.676131893
#Sta/Elev= 30
       0 2455.39    13.5 2453.25    17.4 2450.97    26.6 2443.71    29.9 2443.31
      43  2444.5    62.7 2444.51    75.9 2439.53    95.5 2437.49   144.9 2437.53
   177.6 2436.73   224.9 2438.08   233.4 2437.22   236.6 2434.94   243.2 2433.89
   256.3 2434.88   266.2 2437.18   281.5 2438.18   336.9 2438.22     639 2437.83
   808.3 2438.57   918.5 2440.19   976.7 2439.24  1033.2  2439.5  1050.5 2440.73
    1079 2440.04  1177.8 2440.11  1248.3 2442.69  1328.8    2447    1401 2454.94
#Mann= 7 ,-1 , 0
       0      .1       0      43     .06       0   144.9      .1       0
   233.4    .045       0   266.2      .1       0   336.9    .055       0
    1079      .1       0
#XS Ineff= 2 , 0
          226.48    2437  282.43            2437
Permanent Ineff=
       F       F
Bank Sta=233.4,266.2
XS Rating Curve= 0 ,0
Exp/Cntr(USF)=0,0
Exp/Cntr=0.5,0.3

Type RM Length L Ch R = 1 ,12154   ,492.9,491.5,488.9
XS GIS Cut Line= 2
2042781.39595416 314533.919446112043219.63369209313372.589440581
#Sta/Elev= 30
       0  2455.9    10.9 2453.91    25.4 2444.07      28 2443.28    58.5  2444.5
    63.5 2443.18    70.5 2439.18      74 2438.21   123.1 2436.73   158.2 2437.74
   184.6 2436.26   221.4 2438.12   231.8 2437.13   246.9 2433.48     252 2434.34
   257.1 2437.26   263.4 2437.97   358.1  2436.5   435.3 2436.84   445.8 2435.92
   543.9  2437.2   603.3 2436.11   628.1 2436.84   862.9 2435.78  1006.8 2436.19
  1062.9 2438.34    1119 2438.22  1172.9 2439.59  1206.7 2443.52  1241.3 2451.03
#Mann= 9 ,-1 , 0
       0      .1       0    11.6     .06       0  166.12      .1       0
   231.8    .045       0   257.1    .055       0  304.05      .1       0
  482.24     .07       0   854.4    .055       0  973.43      .1       0
Bank Sta=231.8,257.1
XS Rating Curve= 0 ,0
Exp/Cntr(USF)=0,0
Exp/Cntr=0.3,0.1

Type RM Length L Ch R = 1 ,11662   ,712.1,722.6,713.6
XS GIS Cut Line= 3
2042710.46792944315017.3888652542043043.60475583314944.750008371
 2043394.2750994313426.848378347
#Sta/Elev= 30
       0 2472.81    21.8 2470.83    58.7 2469.35    78.8 2464.03      99 2455.15
   109.1 2454.38   149.4 2443.97   176.3 2439.84     287 2438.42   485.9 2438.16
   505.8  2437.2   517.2 2439.45   547.5 2437.15   732.9 2436.23   806.7 2436.34
   823.6  2437.2   853.9 2435.73   958.3  2437.1   964.5 2436.04   968.4 2433.88
   975.1 2433.09   979.1 2433.26   985.2 2435.85     992 2437.04  1187.3 2435.77
  1668.8 2435.52    1753 2437.09  1779.9 2439.38  1864.1 2442.01  1898.8 2444.04
#Mann= 13 ,-1 , 0
       0     .06       0   53.98    .055       0  153.46     .07       0
  452.27     .06       0  613.87      .1       0   810.7    .055       0
   964.5    .045       0   985.2    .055       0 1008.32      .1       0
 1182.96    .055       0 1296.91     .07       0 1577.55    .055       0
 1759.03      .1       0
Bank Sta=964.5,985.2
XS Rating Curve= 0 ,0
Exp/Cntr(USF)=0,0
Exp/Cntr=0.3,0.1

Type RM Length L Ch R = 1 ,10940   ,702.7,713.9,692.8
XS GIS Cut Line= 3
2043414.31340475315325.4778099612043314.12187801315132.609120998
2043942.82370827 313742.45168756
#Sta/Elev= 30
       0 2445.99   182.6 2439.71   198.1 2437.85   206.8 2439.27   284.9  2438.9
   388.4 2436.82   439.1 2439.77   460.5 2436.58   475.1 2436.27   493.1 2438.19
   511.2 2437.41   523.8 2438.36   827.5 2434.64   929.1 2435.94   951.5 2434.13
   993.5 2436.09  1003.5 2435.05  1015.3 2431.71  1023.4 2434.69  1028.3 2436.03
  1060.6 2434.89  1072.9 2436.62  1184.4 2433.91  1479.8 2433.84    1523 2432.59
  1605.8 2434.27    1649 2438.63  1662.3 2442.29  1677.8 2443.88  1743.1 2462.62
#Mann= 10 ,-1 , 0
       0     .05       0  152.65     .07       0  339.55     .05       0
  379.36     .06       0  547.81    .055       0  1003.5    .045       0
  1023.4    .055       0    1427      .1       0 1428.49    .055       0
 1538.05      .1       0
Bank Sta=1003.5,1023.4
XS Rating Curve= 0 ,0
Exp/Cntr(USF)=0,0
Exp/Cntr=0.3,0.1