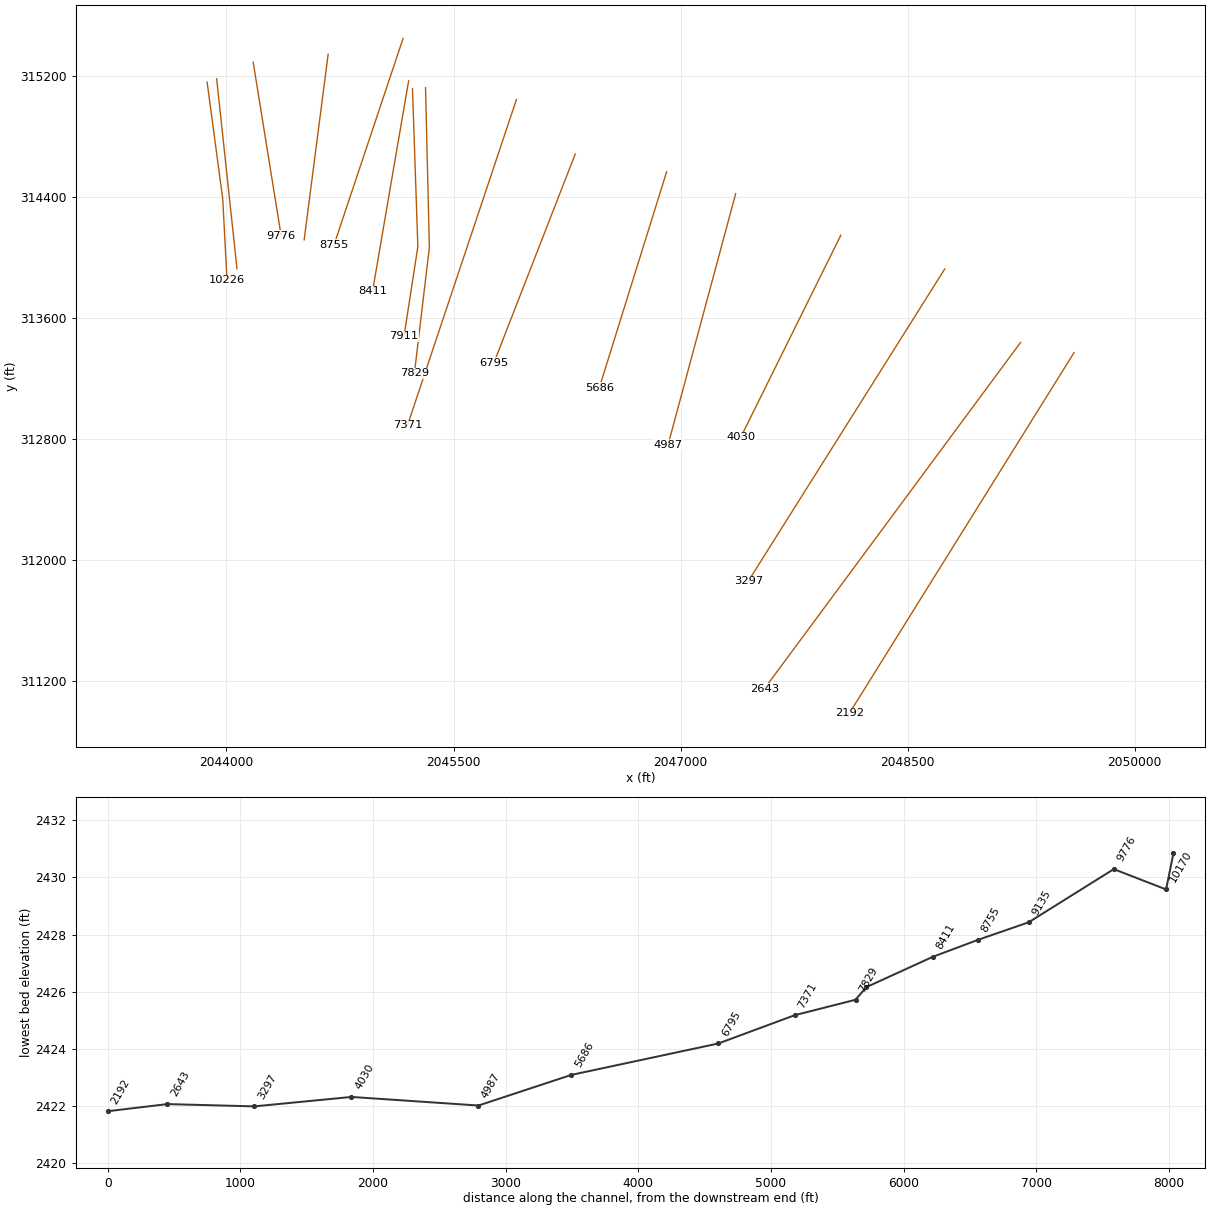
HEC-RAS study BUFFALOCK.prj: BUFFALOCK

--- BUFFALOCK.g01 (geometry) --- (continued)

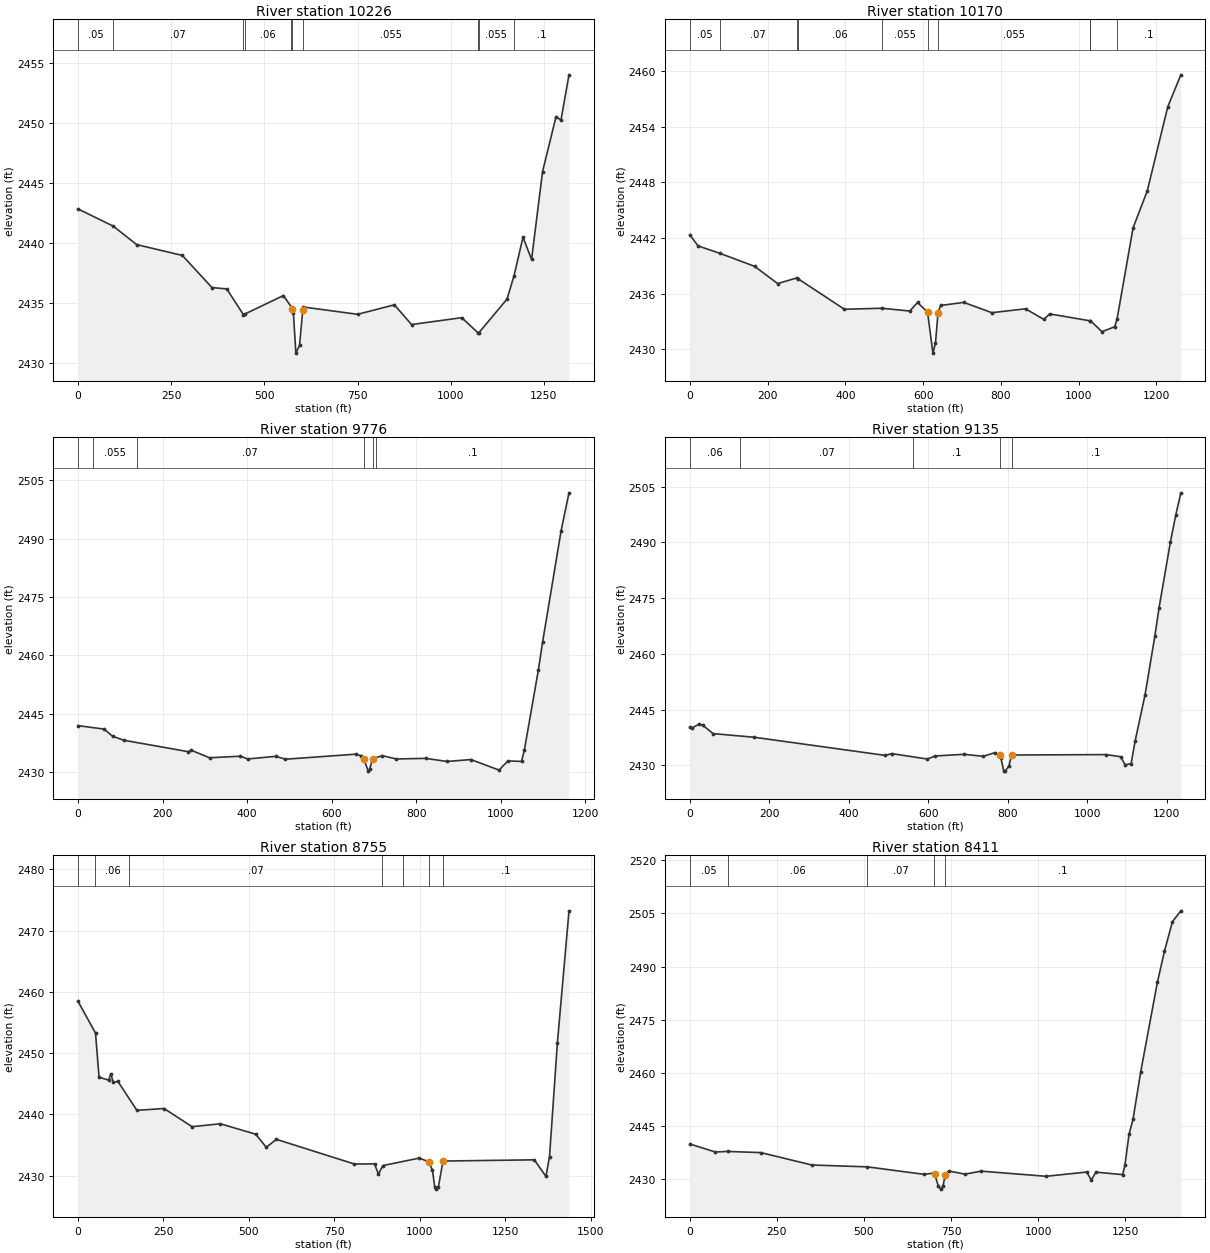
Type RM Length L Ch R = 1 ,10226   ,54.4,55.6,53.1
XS GIS Cut Line= 3
2043872.33785923315158.8402702222043975.51094428 314386.70621438
2044003.80033857313849.207722921
#Sta/Elev= 30
       0 2442.84    94.6 2441.41   157.5 2439.87     280 2438.97   359.4  2436.3
   399.2 2436.18   443.6 2434.05   448.8 2434.11   551.1 2435.63     574 2434.61
   574.6 2434.53   577.9  2434.2   584.5 2430.84   594.4 2431.49     603 2434.42
   604.4 2434.68   750.2 2434.07   848.8 2434.86   894.8 2433.22  1029.5 2433.79
  1072.8 2432.54    1075 2432.52    1151 2435.34  1169.6 2437.26  1193.8 2440.49
  1216.8 2438.64  1246.3 2445.95  1282.5 2450.53  1295.6 2450.23  1317.2    2454
#Mann= 10 ,-1 , 0
       0     .05       0    94.6     .07       0   443.6     .05       0
   448.8     .06       0   570.3    .055       0     574    .045       0
   604.4    .055       0  1072.8      .1       0    1075    .055       0
  1169.6      .1       0
Bank Sta=574.6,603
XS Rating Curve= 0 ,0
Exp/Cntr(USF)=0,0
Exp/Cntr=0.3,0.1

Type RM Length L Ch R = 1 ,10170   ,388.5,394.2,385.7
XS GIS Cut Line= 2
2043935.25137002315181.3656547042044069.67652914313925.885395039
#Sta/Elev= 30
       0 2442.33    21.3 2441.14    77.4 2440.34   166.5 2438.94   225.9 2437.08
   274.5 2437.68   278.7 2437.59   397.5 2434.31   493.1 2434.42   565.7 2434.12
   585.5 2435.04   611.32433.996   625.1 2429.58   631.7 2430.68   638.3 2433.96
   644.9 2434.72   704.3 2435.05   776.8 2433.94   863.2 2434.36   910.1 2433.22
   925.4 2433.81  1028.4 2433.07  1030.1 2433.08  1059.9 2431.89  1092.7 2432.43
  1098.6 2433.25  1139.9  2443.1  1176.2 2447.06    1229 2456.14  1262.7 2459.59
#Mann= 10 ,-1 , 0
       0     .05       0    77.4     .07       0   274.5     .05       0
   278.7     .06       0   493.1    .055       0   611.3    .045       0
   638.3    .055       0  1028.4      .1       0  1030.1    .055       0
  1098.6      .1       0
Bank Sta=611.3,638.3
XS Rating Curve= 0 ,0
Exp/Cntr(USF)=0,0
Exp/Cntr=0.3,0.1

Type RM Length L Ch R = 1 ,9776    ,634.1,641.4,612.7
XS GIS Cut Line= 2
2044176.72082743315290.1602967882044361.34876333314143.843991539
#Sta/Elev= 30
       0 2441.97    61.9 2441.08    81.8 2439.25   108.4 2438.22     261 2435.28
   267.9 2435.64   311.1 2433.72   384.2 2434.12   401.2 2433.41   467.6 2434.09
   490.6 2433.35   656.7 2434.64   670.3 2434.21     676 2433.34   686.6 2430.29
   689.9 2430.82   696.6 2433.51   719.8 2434.26   753.1 2433.41     822 2433.57
   872.7 2432.77   929.2 2433.26   995.7 2430.56  1016.6  2432.9  1048.8 2432.79
  1055.5 2435.68  1088.7 2456.26  1098.7 2463.44  1142.5 2492.04  1161.1 2501.73
#Mann= 6 ,-1 , 0
       0    .055       0   35.88    .055       0  138.42     .07       0
     676    .045       0   696.6     .07       0  704.91      .1       0
Bank Sta=676,696.6
XS Rating Curve= 0 ,0
Exp/Cntr(USF)=0,0
Exp/Cntr=0.3,0.1

Type RM Length L Ch R = 1 ,9135    ,364.4,379.9,360.3
XS GIS Cut Line= 2
2044671.76716103315342.9111356132044513.51464454314117.468572126
#Sta/Elev= 30
       0  2440.3     5.6 2440.03    22.2 2441.05    32.1 2440.84    58.5 2438.53
     162 2437.55   491.9 2432.66   508.4 2433.14   597.7 2431.69   617.6 2432.51
   690.4 2432.96   738.4 2432.42   767.7  2433.4   780.1 2432.71     783 2431.93
   789.6 2428.56   792.9 2428.43   802.9 2429.76   809.5 2432.77  1047.7 2432.88
  1084.1 2432.31  1095.4 2430.12  1110.5 2430.47  1120.4 2436.49  1145.6 2449.05
  1170.1 2464.72  1180.7 2472.38  1209.4 2490.19    1223 2497.49  1235.6 2503.35
#Mann= 5 ,-1 , 0
       0     .06       0  125.95     .07       0  562.59      .1       0
   780.1    .045       0   809.5      .1       0
Bank Sta=780.1,809.5
XS Rating Curve= 0 ,0
Exp/Cntr(USF)=0,0
Exp/Cntr=0.3,0.1

Type RM Length L Ch R = 1 ,8755    ,308.5,344.1,339.7
XS GIS Cut Line= 2
2045167.06397344315448.337669619 2044711.1925268314085.732906033
#Sta/Elev= 30
       0 2458.46    51.3 2453.28    61.7 2446.06    89.4 2445.61    96.3 2446.59
   103.2 2445.24     117 2445.38   172.4 2440.67     252 2440.97   333.9    2438
   416.6 2438.48     520 2436.78   551.1 2434.64   580.6 2435.94   809.1 2431.91
   867.8 2431.94   879.1 2430.28   892.3 2431.66   998.4 2432.88  1026.7 2432.28
  1037.3 2430.88  1044.2 2428.09  1047.6 2427.82  1054.6 2428.17  1068.1  2432.4
  1335.3  2432.6  1369.4 2429.89  1379.8 2433.13  1402.7 2451.59  1436.8 2473.21
#Mann= 7 ,-1 , 0
       0     .05       0   51.21     .06       0  150.12     .07       0
  888.83      .1       0  950.76    .055       0  1026.7    .045       0
  1068.1      .1       0
Bank Sta=1026.7,1068.1
XS Rating Curve= 0 ,0
Exp/Cntr(USF)=0,0
Exp/Cntr=0.3,0.1

Type RM Length L Ch R = 1 ,8411    ,450.2,500.1,465.7
XS GIS Cut Line= 2
2045203.56766402315167.9462775012044965.15323087 313778.04085872
#Sta/Elev= 30
       0 2439.95    73.3 2437.69   108.3 2437.85     204 2437.52   350.7 2434.02
   510.1  2433.5   673.6 2431.38   701.2 2431.78   702.9 2431.53   713.6 2428.09
   720.2 2427.22   726.9 2428.03   732.5 2430.75   733.42431.308   743.5 2432.33
   790.1 2431.45   836.7 2432.29  1023.2 2430.84  1139.7 2432.04    1153 2429.78
  1166.3 2432.01  1242.8 2431.31  1249.6 2433.94  1261.4 2442.75  1272.8  2446.9
    1295 2460.37  1342.7 2485.52  1363.2 2494.37    1386 2502.66  1410.2 2505.71
#Mann= 5 ,-1 , 0
       0     .05       0   108.3     .06       0   510.1     .07       0
   701.2    .045       0   732.5      .1       0
Bank Sta=702.9,733.4
XS Rating Curve= 0 ,0
Exp/Cntr(USF)=0,0
Exp/Cntr=0.5,0.3

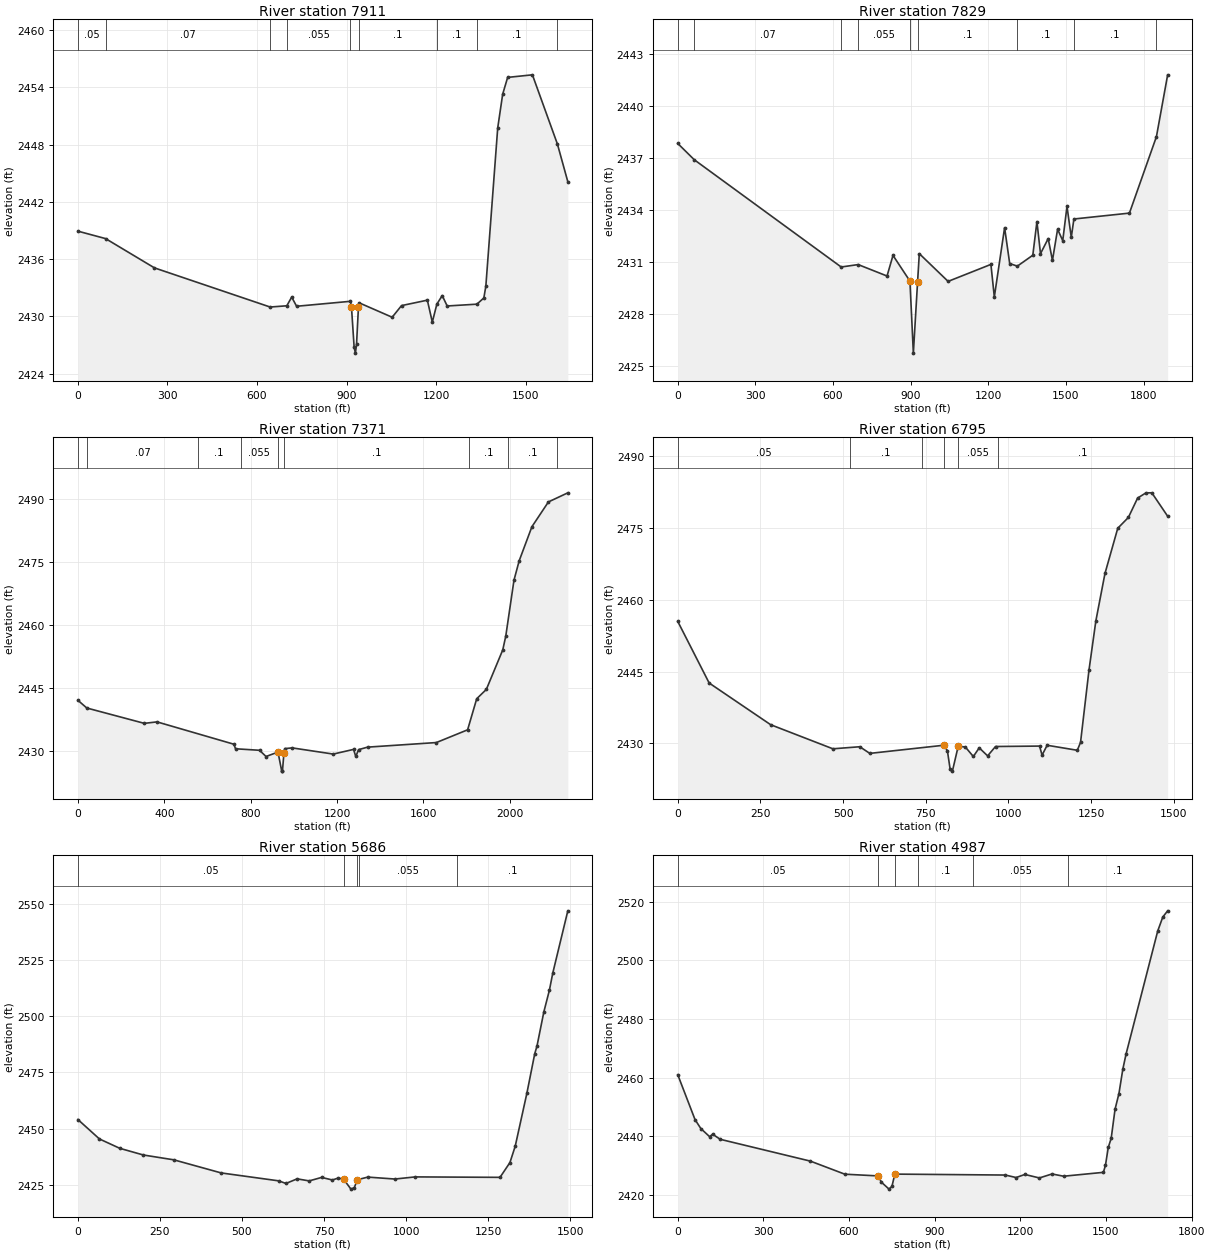
Type RM Length L Ch R = 1 ,7911    ,81.7,81.2,79.4
XS GIS Cut Line= 3
2045228.93090159315114.6834786062045264.43943419 314072.25441452
2045173.13177894313481.290979163
#Sta/Elev= 30
       0 2438.94    92.7 2438.16   256.5 2435.09   643.9 2430.99   699.7 2431.12
   716.1 2432.03   732.5 2431.07     913 2431.59   916.3 2431.01   925.3 2426.75
   929.5 2426.16   933.3 2427.08   939.6 2430.95   942.8 2431.42  1052.6 2429.92
    1084 2431.14  1170.5 2431.71  1187.1 2429.41  1202.3 2431.29  1220.3 2432.19
  1236.9  2431.1  1336.5 2431.29  1359.7 2431.94  1366.4 2433.17  1406.2 2449.76
  1422.8 2453.29  1439.4 2455.05  1522.4 2455.32  1606.2 2448.06    1641 2444.12
#Mann= 9 ,-1 , 0
       0     .05       0    92.7     .07       0   643.9      .1       0
   699.7    .055       0     913    .045       0   942.8      .1       0
  1202.3      .1       0  1336.5      .1       0  1606.2      .1       0
#XS Ineff= 2 , 0
          894.44    2431  959.92            2431
Permanent Ineff=
       F       F
Bank Sta=916.3,939.6
XS Rating Curve= 0 ,0
Exp/Cntr(USF)=0,0
Exp/Cntr=0.5,0.3

Type RM Length L Ch R = 1 ,7829    ,448.2,458.4,445.4
XS GIS Cut Line= 3
2045315.16590933315122.2924498762045340.52914689314067.181767007
2045241.61252038313235.267574744
#Sta/Elev= 30
       0 2437.82    63.8 2436.88   631.6 2430.69   697.2 2430.83   808.8 2430.17
   831.8 2431.36   896.7 2429.89   897.4 2429.84   910.5 2425.72   926.9 2429.85
   933.5 2431.46  1044.8 2429.86  1210.2 2430.84  1223.4 2428.96  1263.1 2432.96
  1282.8 2430.89  1312.4 2430.74  1372.1 2431.37    1388 2433.31  1401.8 2431.46
  1431.6 2432.33    1448 2431.07  1467.9 2432.87  1487.8 2432.21  1504.2 2434.19
  1520.8  2432.4  1530.9 2433.46  1745.5  2433.8  1849.8 2438.21  1893.2 2441.78
#Mann= 9 ,-1 , 0
       0     .05       0    63.8     .07       0   631.6      .1       0
   697.2    .055       0   897.4    .045       0   926.9      .1       0
  1312.4      .1       0  1530.9      .1       0  1849.8      .1       0
Bank Sta=896.7,926.9
XS Rating Curve= 0 ,0
Exp/Cntr(USF)=0,0
Exp/Cntr=0.5,0.3

Type RM Length L Ch R = 1 ,7371    ,550.4,575.8,557.3
XS GIS Cut Line= 2
2045915.99563578315045.0667745142045196.33234397312892.820363064
#Sta/Elev= 30
       0 2442.04    41.2  2440.2   307.6 2436.55   366.4  2436.9   722.7 2431.58
   730.1  2430.5   841.2 2430.14   871.5 2428.66   926.8 2429.72   944.1 2425.18
   947.6 2425.29   954.5 2429.53     958 2430.54   992.5 2430.71  1182.8 2429.24
  1276.8 2430.35  1287.1 2428.68  1300.4  2430.3  1341.9 2430.89  1660.4 2431.98
  1805.2 2435.01  1847.4 2442.41    1892 2444.63  1968.1 2454.04    1982 2457.32
    2020 2470.62  2044.1 2475.24    2103 2483.34  2179.4 2489.24  2269.4 2491.41
#Mann= 9 ,-1 , 0
       0     .05       0   44.21     .07       0  555.37      .1       0
  753.18    .055       0   926.8    .045       0   954.5      .1       0
 1812.84      .1       0 1990.79      .1       0 2221.24      .1       0
Bank Sta=926.8,954.5
XS Rating Curve= 0 ,0
Exp/Cntr(USF)=0,0
Exp/Cntr=0.3,0.1

Type RM Length L Ch R = 1 ,6795    ,1066.8,1108.8,1063.3
XS GIS Cut Line= 2
2046304.23780187 314684.377278272045766.45978212313303.738039872
#Sta/Elev= 30
       0 2455.51      95 2442.62     281  2433.9   469.2 2428.86   550.5 2429.29
   580.9  2427.9   805.5 2429.61   815.6 2428.43   823.8 2424.61   830.7 2424.19
   848.2 2429.37   869.6 2429.25     894 2427.25   911.8 2429.06   937.2 2427.38
   961.1 2429.34  1094.3 2429.43  1101.9 2427.53  1117.2  2429.6  1208.4 2428.55
  1218.2 2430.19  1243.8 2445.33  1264.6 2455.63  1292.1 2465.53  1330.8 2474.99
  1362.9 2477.25  1390.8  2481.3  1416.2  2482.4  1433.9  2482.4  1481.7 2477.51
#Mann= 6 ,-1 , 0
       0     .05       0  520.32      .1       0  739.15    .055       0
   805.5    .045       0   848.2    .055       0  968.03      .1       0
Bank Sta=805.5,848.2
XS Rating Curve= 0 ,0
Exp/Cntr(USF)=0,0
Exp/Cntr=0.3,0.1

Type RM Length L Ch R = 1 ,5686    ,641.3,699.7,650.6
XS GIS Cut Line= 2
2046907.89175044314566.6522343582046463.54232937313141.427766563
#Sta/Elev= 30
       0 2454.05    65.6 2445.41   127.5 2441.25   199.6 2438.27   292.4 2436.12
   436.8 2430.29     612 2426.77     634 2425.61     668 2427.66   704.8 2426.75
   742.6  2428.3   775.4 2427.16   793.8 2428.04   809.9 2427.45     832 2423.09
   842.3 2423.75   851.4 2427.27   883.5 2428.44     966 2427.58  1027.9 2428.53
  1286.3 2428.33  1316.5 2434.91  1332.6 2442.18  1368.1 2465.72  1392.1 2483.33
    1399 2486.78  1419.9 2501.97  1436.8 2511.61  1447.1 2519.24  1492.9  2546.9
#Mann= 5 ,-1 , 0
       0     .05       0   809.9    .045       0   851.4     .05       0
  855.04    .055       0  1154.3      .1       0
Bank Sta=809.9,851.4
XS Rating Curve= 0 ,0
Exp/Cntr(USF)=0,0
Exp/Cntr=0.3,0.1

Type RM Length L Ch R = 1 ,4987    ,894.3,956.8,918.7
XS GIS Cut Line= 2
2047363.76319709314421.3745205932046917.66042431312764.457147225
#Sta/Elev= 30
       0 2461.02    60.5 2445.72    80.9 2442.67   111.5 2439.91   122.2 2440.74
   148.9    2439   464.8 2431.56   585.3 2427.11   702.7 2426.52   712.9 2424.42
   740.1 2422.02   750.2 2422.96   760.4 2427.14  1147.5 2426.82  1185.1 2425.97
  1215.7 2427.02  1266.7 2425.83  1310.8 2427.19  1351.6 2426.42  1490.9 2427.74
  1498.2 2430.22  1507.9 2436.24  1518.1 2439.31  1531.7 2449.28  1545.3 2454.59
  1558.9 2462.91  1570.4 2468.13  1681.2 2510.03  1698.9 2514.77  1715.9 2516.88
#Mann= 6 ,-1 , 0
       0     .05       0   702.7    .045       0   760.4     .07       0
  841.94      .1       0 1033.45    .055       0 1368.58      .1       0
Bank Sta=702.7,760.4
XS Rating Curve= 0 ,0
Exp/Cntr(USF)=0,0
Exp/Cntr=0.3,0.1

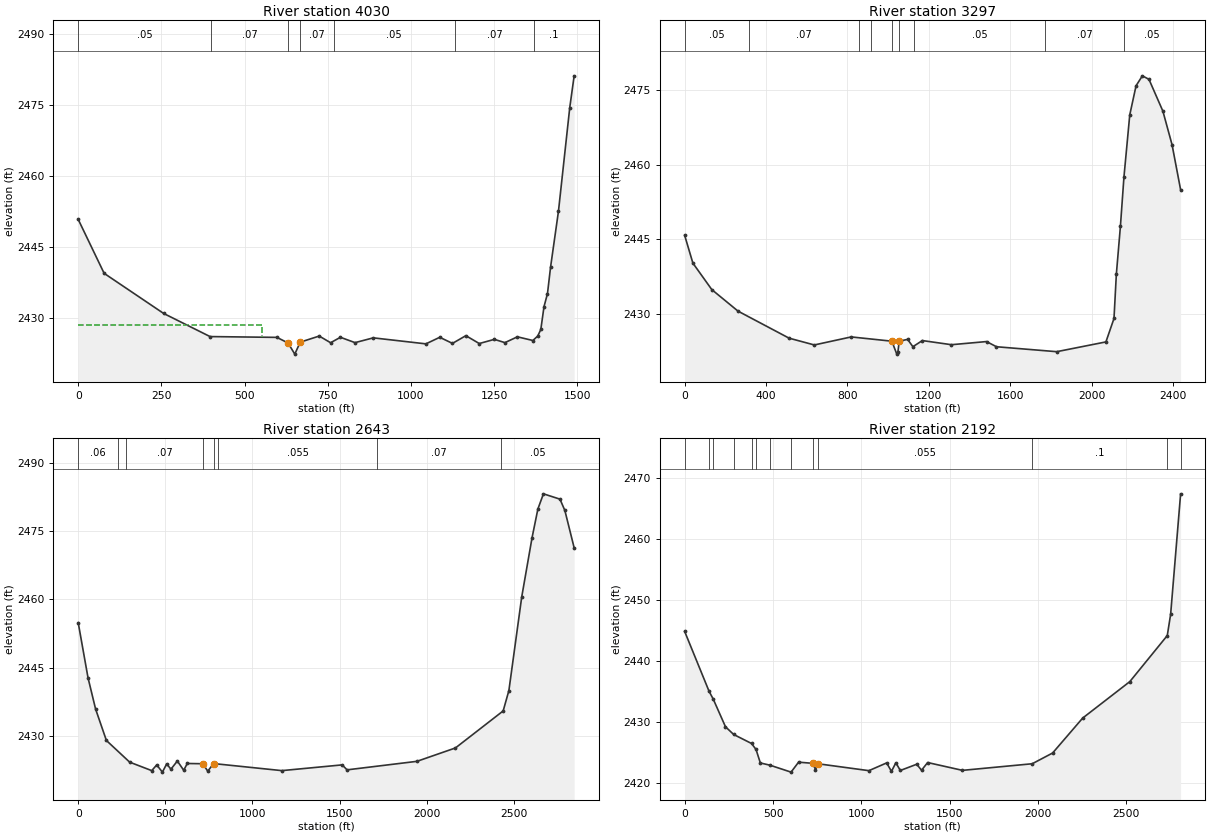
Type RM Length L Ch R = 1 ,4030    ,736.6,732.7,732.9
XS GIS Cut Line= 2
2048058.54814235314147.3012176782047396.78929294312811.414194554
#Sta/Elev= 30
       0  2450.8    77.9  2439.4   256.8 2430.92   396.3 2426.03   597.2 2425.86
   630.8 2424.68     651 2422.32   667.4 2424.85   724.5 2426.14   758.7 2424.73
   788.2 2425.88   832.1 2424.75     887 2425.76  1045.2 2424.49  1086.8 2425.88
    1125 2424.59  1165.3 2426.22  1205.6 2424.56  1250.9 2425.44  1282.7 2424.75
  1320.2 2425.98  1366.7  2425.2  1381.3 2426.14  1390.6 2427.53  1400.2 2432.36
  1410.6  2435.1  1419.8 2440.66  1443.6  2452.5  1477.6 2474.45  1490.8 2481.15
#Mann= 7 ,-1 , 0
       0     .05       0   399.5     .07       0   630.8    .045       0
   667.4     .07       0  767.45     .05       0 1132.29     .07       0
 1369.91      .1       0
#XS Ineff= 2 , 0
          551.02 2428.48
Permanent Ineff=
       F       F
Bank Sta=630.8,667.4
XS Rating Curve= 0 ,0
Exp/Cntr(USF)=0,0
Exp/Cntr=0.3,0.1

Type RM Length L Ch R = 1 ,3297    ,661.7,654.4,646
XS GIS Cut Line= 2
2048745.04564035 313924.653380492047446.75208606311861.298564998
#Sta/Elev= 30
       0  2445.8    40.4 2440.24   133.4 2434.93   262.4 2430.61   513.3 2425.19
   637.3 2423.83   818.5 2425.44  1018.32424.585  1042.7 2421.99  1048.2 2422.42
  1054.6 2424.58  1095.7 2424.95  1121.8 2423.48  1168.3 2424.71  1311.3 2423.88
  1483.8 2424.51  1532.7 2423.47  1828.8 2422.48  2070.6 2424.44  2110.3 2429.14
  2121.9 2438.02  2141.9 2447.65  2159.3 2457.54  2187.8 2469.98  2218.8 2475.82
  2249.8 2477.81  2282.3  2477.1  2350.6 2470.73  2395.6 2464.01  2437.8 2454.96
#Mann= 9 ,-1 , 0
       0     .05       0   314.8     .07       0  858.06    .055       0
  915.19     .07       0 1018.32    .045       0  1054.6     .07       0
 1125.55     .05       0 1771.35     .07       0 2158.49     .05       0
Bank Sta=1018.3,1054.6
XS Rating Curve= 0 ,0
Exp/Cntr(USF)=0,0
Exp/Cntr=0.3,0.1

Type RM Length L Ch R = 1 ,2643    ,435.5,451,452.2
XS GIS Cut Line= 2
2049246.00327402313439.1574021792047552.82831883311150.306712582
#Sta/Elev= 30
       0 2454.88    56.3 2442.79    99.7 2435.93   161.8 2429.02   295.4 2424.26
   422.1  2422.4   450.7 2423.65   483.3 2422.07   507.8 2423.87   532.4 2422.72
     569 2424.51   605.7 2422.48   626.1 2423.97   715.4 2423.91   743.6 2422.28
   777.1 2423.95  1168.9  2422.4  1515.3 2423.66  1543.4 2422.57  1944.6 2424.44
  2165.6 2427.38  2439.5 2435.51  2472.3 2439.98  2546.2 2460.58  2605.4 2473.56
  2638.9 2479.86  2670.7 2483.18  2765.6 2482.01  2793.7 2479.52    2847 2471.33
#Mann= 8 ,-1 , 0
       0     .06       0  228.59     .05       0  276.72     .07       0
   715.4    .045       0   777.1     .07       0  802.89    .055       0
 1714.21     .07       0 2429.24     .05       0
Bank Sta=715.4,777.1
XS Rating Curve= 0 ,0
Exp/Cntr(USF)=0,0
Exp/Cntr=0.3,0.1

Type RM Length L Ch R = 1 ,2192    ,609.8,619.7,608.3
XS GIS Cut Line= 2
2049598.76462405313371.3294142922048114.60412524310988.899553597
#Sta/Elev= 30
       0 2444.84   138.2 2435.04   161.8 2433.76     231 2429.24   277.4 2427.98
   378.3 2426.51   403.8 2425.53   428.3 2423.32   482.2 2422.96   602.1 2421.82
   644.6 2423.45   725.8 2423.26   740.3 2422.25   756.7 2423.18  1042.7 2422.06
  1143.2 2423.33  1170.3 2421.94  1195.2 2423.35  1220.5 2422.09  1313.3 2423.11
  1340.5 2422.13  1375.1 2423.39  1572.3 2422.11  1966.9 2423.19  2082.5 2424.95
  2252.7 2430.67  2519.6 2436.64  2731.4 2444.17  2750.4 2447.65  2806.9 2467.37
#Mann= 13 ,-1 , 0
       0    .055       0   138.2     .06       0   161.8    .055       0
   277.4     .05       0   378.3     .06       0   403.8     .05       0
   482.2     .07       0   602.1    .055       0   725.8    .045       0
   756.7    .055       0  1966.9      .1       0  2731.4     .05       0
  2806.9    .055       0
Bank Sta=725.8,756.7
XS Rating Curve= 0 ,0
Exp/Cntr(USF)=0,0
Exp/Cntr=0.5,0.3