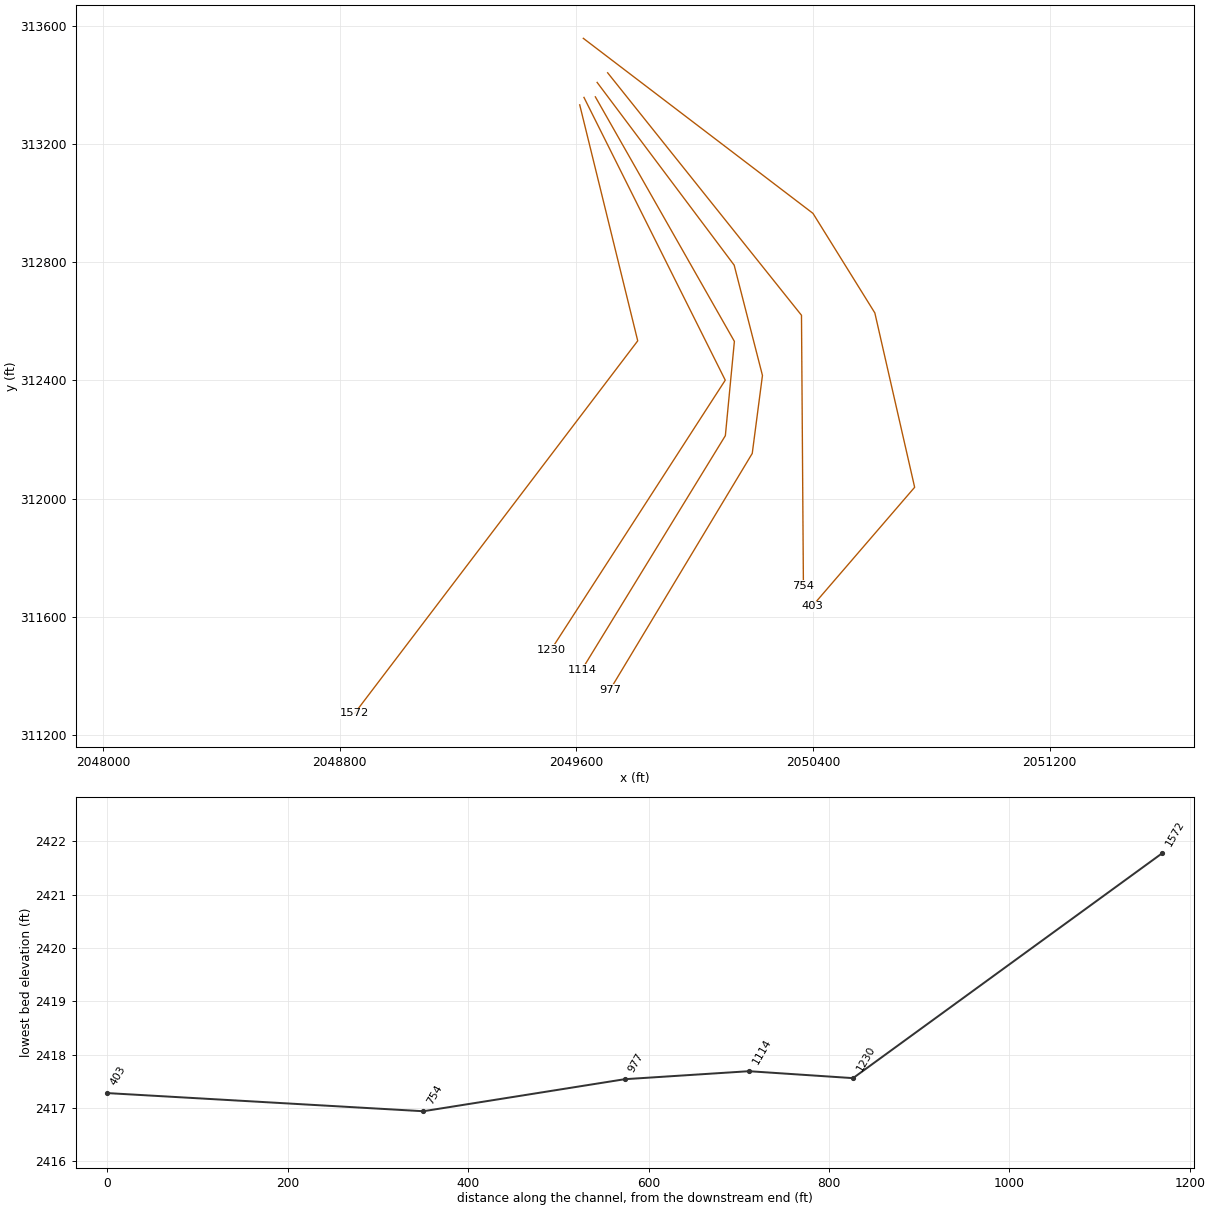
HEC-RAS study BUFFALOCK.prj: BUFFALOCK

--- BUFFALOCK.g01 (geometry) --- (continued)

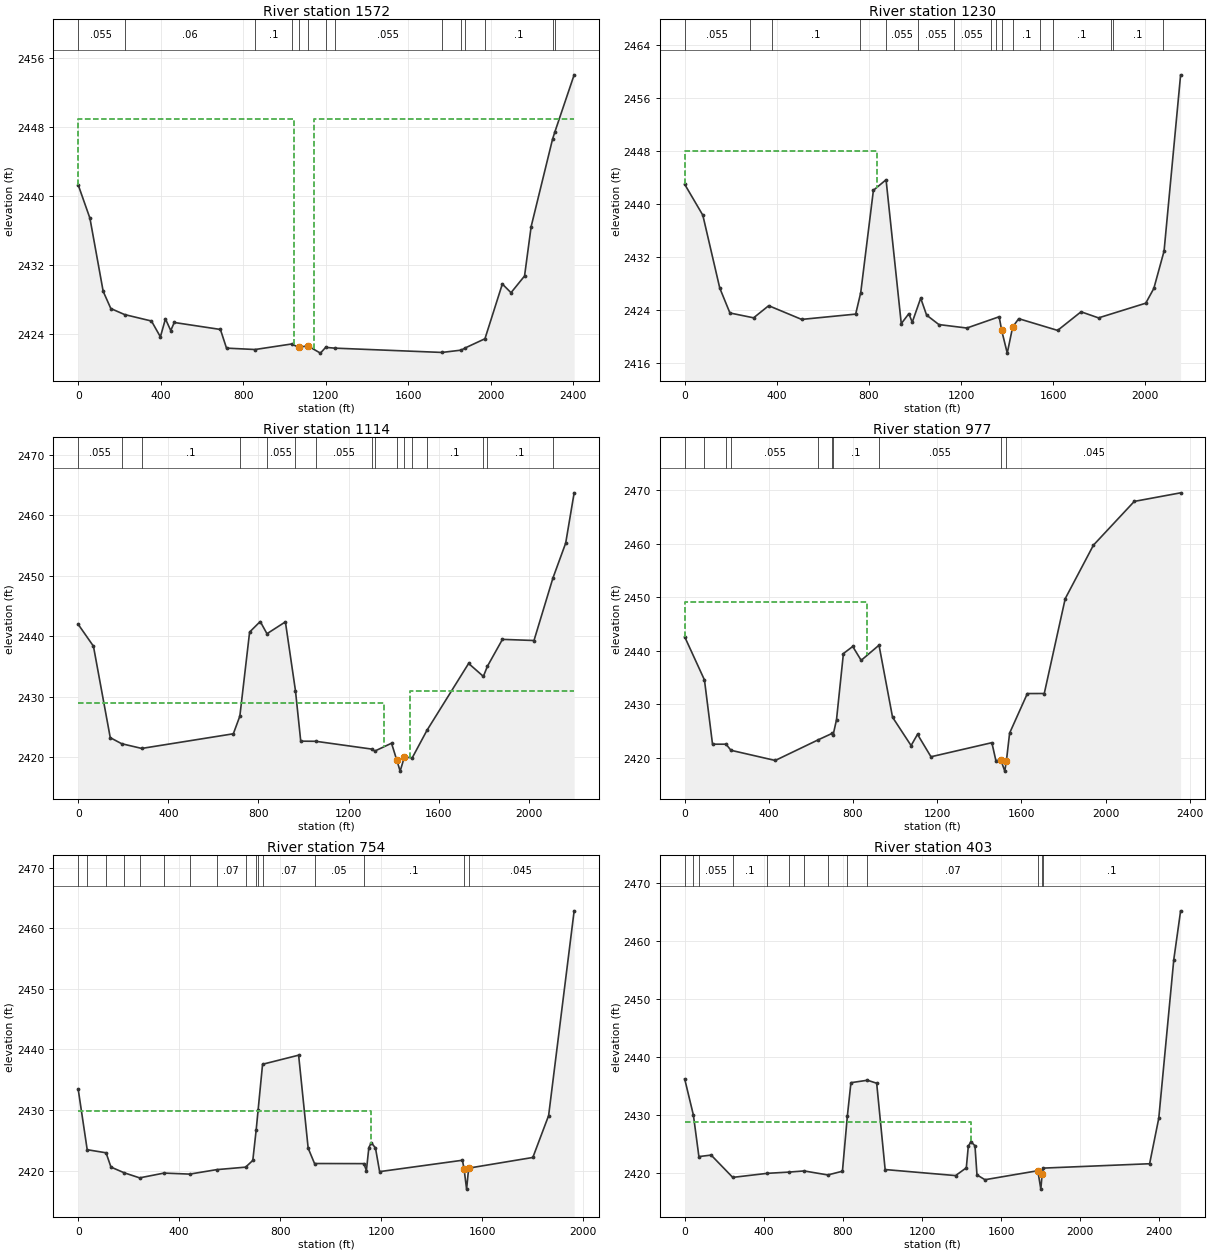
Type RM Length L Ch R = 1 ,1572    ,341,342.4,344.2
XS GIS Cut Line= 3
2049611.20385987313332.1307623762049807.32249365312533.899978272
2048850.09678183311273.706663461
#Sta/Elev= 30
       0 2441.31    56.8 2437.44     121 2428.95   158.1 2426.95   224.9 2426.25
   355.1  2425.5   398.5 2423.66   422.9 2425.75   448.7 2424.39   465.6 2425.33
   689.4 2424.52     719 2422.35   857.5 2422.19  1034.2 2422.83  1069.5 2422.44
  1112.7 2422.62  1174.3 2421.77  1199.7 2422.44  1243.1 2422.35  1763.6 2421.85
  1857.3 2422.12  1877.7 2422.39    1972 2423.44  2056.3  2429.8  2098.4 2428.79
    2164 2430.73    2196 2436.47  2299.8 2446.63  2310.6 2447.44  2404.5  2454.1
#Mann= 14 ,-1 , 0
       0    .055       0   224.9     .06       0   857.5      .1       0
  1034.2    .055       0  1069.5    .045       0  1112.7    .055       0
  1199.7      .1       0  1243.1    .055       0  1763.6     .07       0
  1857.3    .055       0  1877.7     .07       0    1972      .1       0
  2299.8     .06       0  2310.6      .1       0
#XS Ineff= 2 , 0
         1048.26    2449 1140.93            2449
Permanent Ineff=
       F       F
Bank Sta=1069.5,1112.7
XS Rating Curve= 0 ,0
Exp/Cntr(USF)=0,0
Exp/Cntr=0.5,0.3

Type RM Length L Ch R = 1 ,1230    ,113.6,115.4,113.7
XS GIS Cut Line= 3
2049625.55873825313357.3465042852050103.24855609312400.854409837
2049514.84251384311489.669499338
#Sta/Elev= 30
       0 2443.05    78.8 2438.38   152.4 2427.38   196.5 2423.62   299.3 2422.89
   364.9 2424.72   507.9 2422.65   742.6 2423.45   764.6  2426.7   819.6 2442.14
   874.6 2443.73   940.6 2422.01   973.6 2423.52   988.3 2422.22    1025 2425.86
  1050.6  2423.3  1104.1 2421.87  1225.4 2421.35  1365.8 2423.05  1376.6    2421
  1400.9 2417.56  1424.42421.506  1450.7 2422.76  1619.6 2420.99  1721.4  2423.8
  1797.2 2422.88  2002.4  2425.1  2037.5 2427.33  2081.9 2432.96  2153.8 2459.57
#Mann= 16 ,-1 , 0
       0    .055       0  284.32     .06       0  377.35      .1       0
  762.86     .06       0  875.21    .055       0 1013.44    .055       0
 1167.66    .055       0 1329.55     .06       0 1351.79    .055       0
  1376.6    .045       0  1424.4      .1       0 1543.01     .05       0
 1599.55      .1       0 1853.59    .055       0 1861.49      .1       0
 2076.67     .06       0
#XS Ineff= 2 , 0
          833.94    2448
Permanent Ineff=
       F       F
Bank Sta=1376.6,1424.4
XS Rating Curve= 0 ,0
Exp/Cntr(USF)=0,0
Exp/Cntr=0.5,0.3

Type RM Length L Ch R = 1 ,1114    ,129.6,137.7,134.4
XS GIS Cut Line= 4
2049664.05743654313359.2644087322050134.11690616312532.081835565
2050103.59356398 312213.112909752049618.27242326311421.032180093
#Sta/Elev= 30
       0 2441.94    67.6 2438.33   142.2 2423.22   192.8 2422.22   281.8 2421.44
   688.4 2423.86   717.3 2426.78   760.6 2440.67   807.8 2442.41   837.6 2440.39
   919.4 2442.35   964.1 2430.97   987.5 2422.64  1054.3 2422.62  1302.9 2421.33
  1316.4 2421.01  1390.4  2422.3  1412.92419.601  1428.6 2417.69  1447.3    2420
  1482.4  2419.9  1547.8 2424.44  1732.5 2435.48  1797.9 2433.34  1816.1 2435.03
  1882.6 2439.46  2022.6 2439.27  2106.7  2449.6  2163.2 2455.36  2200.8 2463.67
#Mann= 16 ,-1 , 0
       0    .055       0   192.8     .06       0   281.8      .1       0
   717.3     .06       0   837.6    .055       0   964.1    .055       0
  1054.3    .055       0  1302.9     .06       0  1316.4    .055       0
  1412.9    .045       0  1447.3      .1       0  1482.4     .05       0
  1547.8      .1       0  1797.9    .055       0  1816.1      .1       0
  2106.7     .06       0
#XS Ineff= 2 , 0
         1358.81    2429  1472.2            2431
Permanent Ineff=
       F       F
Bank Sta=1412.9,1447.3
XS Rating Curve= 0 ,0
Exp/Cntr(USF)=0,0
Exp/Cntr=0.5,0.3

Type RM Length L Ch R = 1 ,977     ,218,223.2,232.8
XS GIS Cut Line= 5
2049670.08534881313408.0701964132050133.41293928 312789.90336167
 2050229.0077164312416.8669356172050194.51678332 312153.11274149
2049713.67259864311353.734645442
#Sta/Elev= 30
       0 2442.62      94 2434.56   132.3 2422.57   196.6 2422.57   219.8 2421.43
   430.3 2419.53   635.3  2423.4   700.9 2424.59   705.7 2424.37   721.4 2427.12
   754.2 2439.49   798.5 2440.81   838.6 2438.22   923.4 2441.05   987.7  2427.6
  1075.8 2422.31  1106.3 2424.41  1170.3 2420.22  1459.7 2422.85  1478.9 2419.47
  1501.9 2419.66    1521 2417.54  1528.7 2419.46    1544 2424.64  1628.2 2432.02
  1708.6 2432.03  1808.2 2449.74  1942.2 2459.72  2136.3 2467.89  2356.5 2469.49
#Mann= 10 ,-1 , 0
       0    .055       0      94    .055       0   196.6    .055       0
   219.8    .055       0   635.3    .045       0   700.9    .055       0
   705.7      .1       0   923.4    .055       0  1501.9    .045       0
  1528.7    .045       0
#XS Ineff= 2 , 0
          866.86 2449.06
Permanent Ineff=
       F       F
Bank Sta=1501.9,1528.7
XS Rating Curve= 0 ,0
Exp/Cntr(USF)=0,0
Exp/Cntr=0.5,0.3

Type RM Length L Ch R = 1 ,754     ,347.6,350.3,351.8
XS GIS Cut Line= 3
2049705.62687432313440.6499307522050360.98037873312620.378225453
2050367.50159464311706.030513874
#Sta/Elev= 30
       0 2433.42    35.6 2423.45   110.3 2422.94   129.7 2420.58   182.6 2419.63
   243.3  2418.8   339.7 2419.59   441.8 2419.42   548.5 2420.16     663 2420.57
   691.5 2421.68     705 2426.76   712.5 2429.99   730.2 2437.56     873 2439.06
   910.8  2423.7     936 2421.17  1131.5 2421.15  1141.4 2420.01  1151.2 2423.81
    1161 2424.61  1177.4 2423.73  1193.8 2419.83  1521.9 2421.71  1528.5  2420.2
  1538.3 2416.94  1546.52420.408  1800.7 2422.17  1863.2 2429.09  1964.3  2462.9
#Mann= 16 ,-1 , 0
       0    .055       0    35.6    .055       0   110.3    .055       0
   182.6      .1       0   243.3     .06       0   339.7    .055       0
   441.8     .06       0   548.5     .07       0     663      .1       0
     705     .07       0   712.5    .045       0   730.2     .07       0
     936     .05       0  1131.5      .1       0  1528.5    .045       0
  1546.5    .045       0
#XS Ineff= 2 , 0
         1158.74 2429.77
Permanent Ineff=
       F       F
Bank Sta=1528.5,1546.5
XS Rating Curve= 0 ,0
Exp/Cntr(USF)=0,0
Exp/Cntr=0.3,0.1

Type RM Length L Ch R = 1 ,403     ,,,
XS GIS Cut Line= 5
2049623.38924902313557.1858306232050399.82608124312965.108428885
2050609.00312737 312628.297930892050743.57931147312038.517144921
2050397.64810006311636.626472841
#Sta/Elev= 30
       0 2436.25    44.1 2430.02    71.9 2422.88   133.8 2423.14     243  2419.3
   418.4    2420   526.3 2420.21   604.1 2420.41   723.8 2419.72   797.8 2420.36
   822.8 2429.89   840.8  2435.6   924.2 2436.02     971 2435.51  1013.8 2420.65
  1370.1 2419.61  1424.3 2420.95  1434.4 2424.68  1447.9 2425.44  1468.1 2424.74
  1478.2 2419.73  1518.6  2418.9  1785.9 2420.45  1801.2 2417.28    1808 2419.95
  1814.5  2420.9  2351.3 2421.65  2397.6 2429.48  2473.6 2456.79  2508.1 2465.18
#Mann= 13 ,-1 , 0
       0    .055       0    44.1    .055       0    71.9    .055       0
     243      .1       0   418.4     .06       0   526.3    .055       0
   604.1     .06       0   723.8     .07       0   822.8      .1       0
   924.2     .07       0  1785.9    .045       0    1808    .045       0
  1814.5      .1       0
#XS Ineff= 2 , 0
         1448.43 2428.77
Permanent Ineff=
       F       F
Bank Sta=1785.9,1808
XS Rating Curve= 0 ,0
Exp/Cntr(USF)=0,0
Exp/Cntr=0.3,0.1
LCMann Table=0

Chan Stop Cuts=-1
Use User Specified Reach Order=0
Composite Channel Slope=5